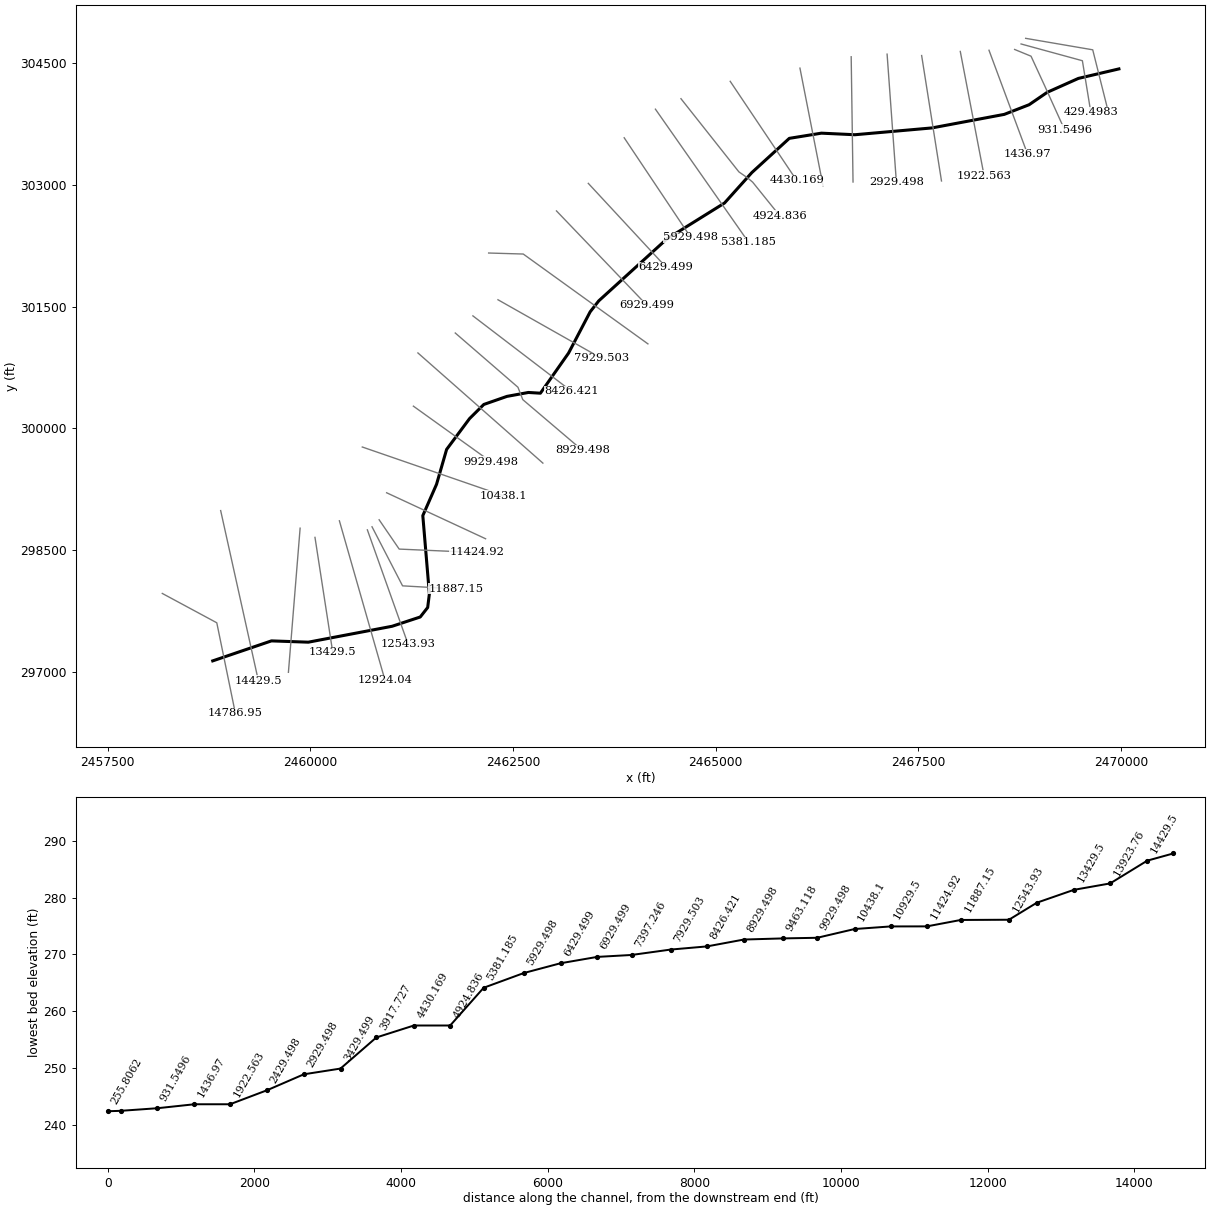
--- Shenandoah2.prj (project) ---

Proj Title=Shenandoah2
Current Plan=p02
Default Exp/Contr=0.3,0.1
English Units
Geom File=g01
Geom File=g02
Flow File=f01
Plan File=p01
Plan File=p02
Y Axis Title=Elevation
X Axis Title(PF)=Main Channel Distance
X Axis Title(XS)=Station
BEGIN DESCRIPTION:
END DESCRIPTION:
DSS Export Rating Curves= 0
DSS Export Rating Curve Sorted= 0
DSS Export Volume Flow Curves= 0
DXF OffsetX= 0
DXF OffsetY= 0
DXF ScaleX= 1
DXF ScaleY= 10

--- Shenandoah2.p02 (plan) ---

Plan Title=Plan 02
Program Version=4.10
Short Identifier=Plan 01
Geom File=g02
Flow File=f01
Subcritical Flow
K Sum by GR= 0
Std Step Tol= 0.01
Critical Tol= 0.01
Num of Std Step Trials= 20
Max Error Tol= 0.3
Flow Tol Ratio= 0.001
Split Flow NTrial= 30
Split Flow Tol= 0.02
Split Flow Ratio= 0.02
Log Output Level= 0
Friction Slope Method= 1
Unsteady Friction Slope Method= 2
Unsteady Bridges Friction Slope Method= 1
Parabolic Critical Depth
Global Vel Dist= 0 , 0 , 0
Global Log Level= 0
CheckData=True
Encroach Param=-1 ,0,0, 0
Computation Interval=1HOUR
Output Interval=1HOUR
Run HTab= 0
Run UNet= 0
Run PostProcess= 0
Run WQNet= 0
UNET Theta= 1
UNET Theta Warmup= 1
UNET ZTol= 0.02
UNET ZSATol= 0.05
UNET MxIter= 20
UNET MaxInSteps= 0
UNET DtIC= 0
UNET DtMin= 0
UNET MaxCRTS= 20
UNET WFStab= 2
UNET SFStab= 1
UNET WFX= 1
UNET SFX= 1
UNET DSS MLevel= 4
UNET DZMax Abort= 100
UNET Convert EG Bridges= 0
UNET Use Existing IB Tables=-1
UNET Froude Reduction=False
UNET Froude Limit= 1
UNET Froude Power= 10
UNET Time Slicing=0,0, 5
UNET Junction Losses=0
Instantaneous Interval=1HOUR
Write IC File= 0
Write IC File at Sim End=0
Echo Input=False
Echo Parameters=False
Echo Output=False
Write Detailed= 0
WQ AD Non Conservative
WQ ULTIMATE=-1
WQ Max Comp Step=1HOUR
WQ Output Interval=15MIN
WQ Output Selected Increments= 0
WQ Output face flow=0
WQ Output face velocity=0
WQ Output face area=0
WQ Output face dispersion=0
WQ Output cell volume=0
WQ Output cell surface area=0
WQ Output cell continuity=0
WQ Output cumulative cell continuity=0
WQ Output face conc=0
WQ Output face dconc_dx=0
WQ Output face courant=0
WQ Output face peclet=0
WQ Output face adv mass=0
WQ Output face disp mass=0
WQ Output cell mass=0
WQ Output cell source sink temp=0
WQ Output cell source sink nsm=0
WQ Output MaxMinRange=-1
WQ Daily Max Min Mean=-1
WQ Daily Range=0
WQ Daily Time=0
WQ Create Restart=0
WQ Fixed Restart=0
WQ System Summary=0
WQ Use Fixed Temperature=0
Sorting and Armoring Iterations= 10
XS Update Threshold= 0.02
Hydraulics Update Threshold= 0.02
Energy Slope Method= 1
Volume Change Method= 0
XS Weighting Method= 0
Number of US Weighted Cross Sections= 1
Number of DS Weighted Cross Sections= 1
Upstream XS Weight=0.25
Main XS Weight=0.5
Downstream XS Weight=0.25
Number of DS XS's Weighted with US Boundary= 1
Upstream Boundary Weight= 1
Weight of XSs Associated with US Boundary= 0
Number of US XS's Weighted with DS Boundary= 1
Downstream Boundary Weight= 0.5
Weight of XSs Associated with DS Boundary= 0.5
Sediment Output Level= 4
Mass or Volume Output= 0
Output Increment Type= 1
Profile and TS Output Increment= 10
XS Output Flag= 0
XS Output Increment= 10
Disregard all LS=0
Disregard all Conn=0
Disregard all Breaches=0
Disregard all Pumps=0

--- Shenandoah2.p01 (plan) ---

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Plan Title=Plan 01
Geom File=g01
Flow File=f01

--- Shenandoah2.f01 (steady flow) ---

Flow Title=Shenandoah2
Program Version=4.10
Number of Profiles= 1
Profile Names=PF 1
River Rch & RM=ShenandoahRiver,Reach2          ,14786.95
  177362
Boundary for River Rch & Prof#=ShenandoahRiver,Reach2          , 1
Up Type= 0
Dn Type= 1
Dn Known WS=302.64
DSS Import GetInterval= 0
DSS Import GetPeak= 0
DSS Import FillOption= 0

--- Shenandoah2.g02 (geometry) ---

Geom Title=chanel
Program Version=4.10

River Reach=ShenandoahRiver ,Reach2
Reach XY= 30
2458797.52064428297132.2232446072459521.82628228297378.750966772
2459976.52255136297362.786103681 2461010.7813096297559.128886849
2461357.31998661297673.5075951072461448.91888477297790.542137936
2461469.74299011297958.6120117752461388.83895244298923.416184515
2461558.28447969299310.1745973532461682.41644928299739.862058192
2461965.44278611300120.064381763 2462141.3738647300294.442970023
2462426.68431769300393.9191490262462691.14671527300442.260587767
2462839.35803303300433.2848839312463187.19099878300928.722213268
2463453.16290778301436.8383230272463559.15252519301571.951241776
2464399.63050303 302336.061590182465110.14614236302778.270023346
2465447.49914218303154.0041800142465909.62977961303575.987916097
2466305.52236052303639.984507263 2466719.1914807 303620.60134393
2467669.25847819303704.5680395222468561.44206128303871.632337943
2468868.17241894303990.9523092662469091.05353487304143.696098268
2469475.16825219304315.1370283512469975.38542761304432.324458018

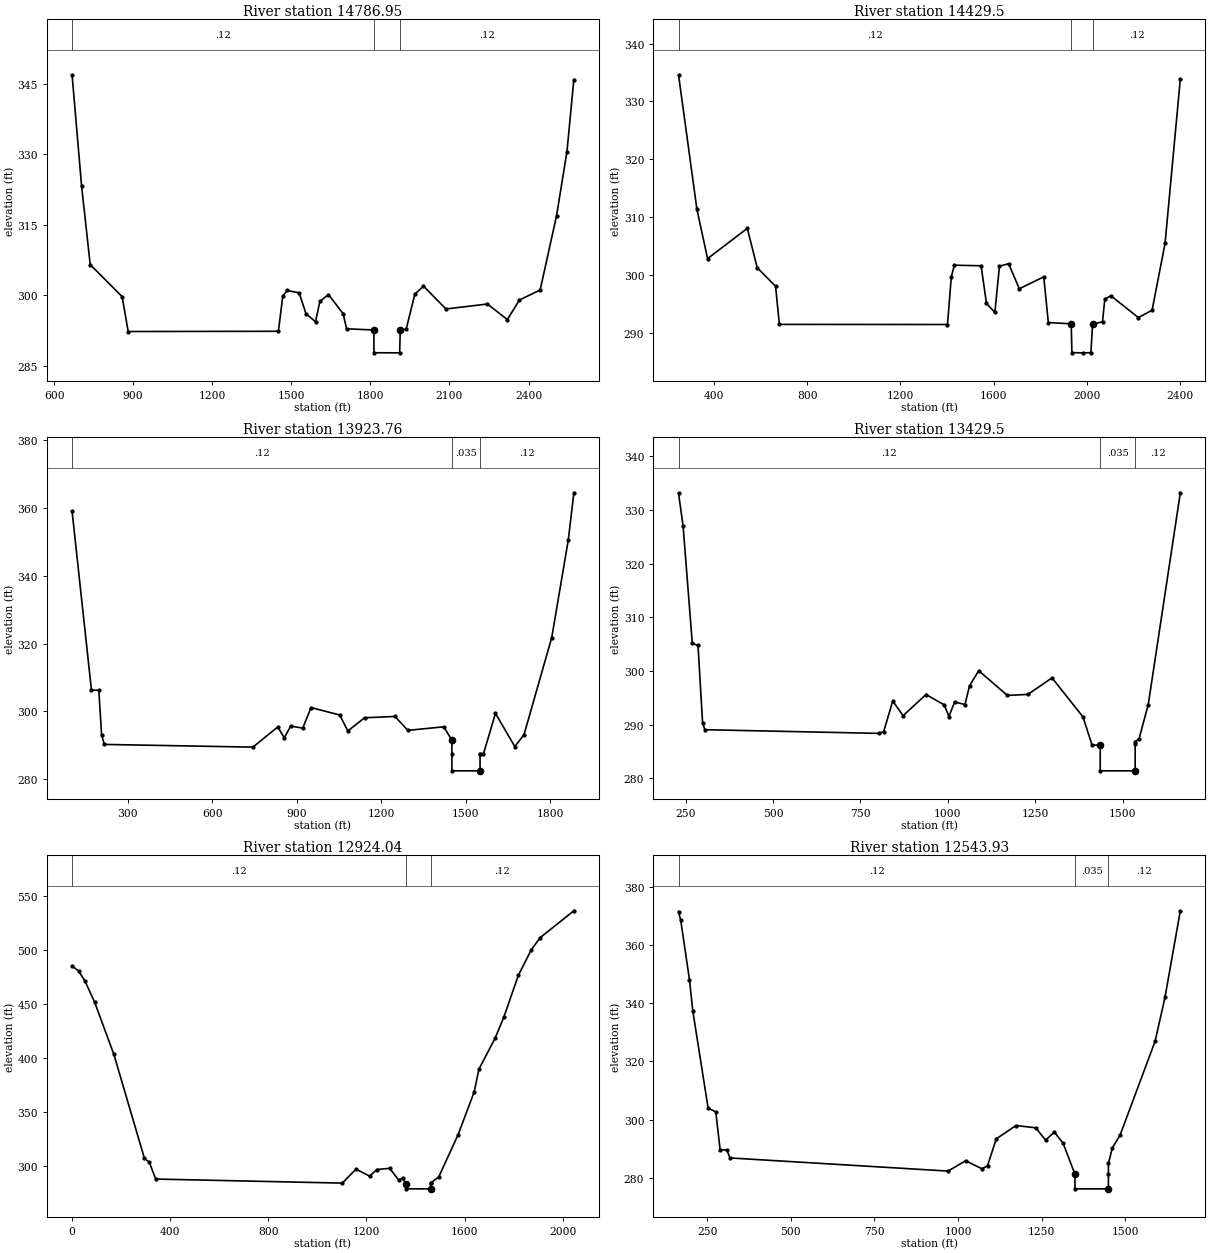
Type RM Length L Ch R = 1 ,14786.95,356.63,357.45,358.22
XS GIS Cut Line= 4
2458175.36619098297963.7467292332458847.45197485297602.020861432
2458916.60111478 297265.247584852459076.84678845296484.810735247
#Sta/Elev= 30
  668.25  346.88  704.28  323.29  737.04  306.55  858.24  299.73  881.17  292.33
 1451.14  292.38 1467.51   299.8 1483.88  301.05 1529.72  300.55 1555.92  296.09
 1591.94   294.4 1608.31  298.71 1641.05  300.19 1696.71  296.11 1709.81  292.91
 1813.45  292.65 1813.54  287.82 1910.99   287.8 1913.45  292.65 1935.95  292.85
 1968.74  300.28 2001.52  301.98 2086.77  297.12 2244.15  298.17 2319.56  294.86
 2365.46  299.02 2444.14  301.16 2506.44  316.95 2545.78  330.55 2572.01  345.87
#Mann= 3 , 0 , 0
  668.25     .12       0 1813.45    .035       0 1913.45     .12       0
Bank Sta=1813.45,1913.45
XS Rating Curve= 0 ,0
Exp/Cntr=0.3,0.1

Type RM Length L Ch R = 1 ,14429.5 ,520.55,505.74,490.63
XS GIS Cut Line= 3
 2458895.2024841 298985.763772322459228.01190928297485.996815264
2459360.93040653296885.634468848
#Sta/Elev= 30
  248.95  334.62  327.56  311.39  373.42  302.82  543.75  308.05  586.33  301.24
  664.95  298.03  681.33  291.44 1401.96  291.42 1418.34  299.69 1431.44  301.68
 1546.09  301.58 1569.01  295.07 1605.05  293.51  1624.7   301.5 1664.01  301.94
 1709.86   297.6 1814.64  299.67 1834.27  291.76 1932.39  291.54 1935.37  286.55
 1982.13  286.52  2016.8  286.55 2023.97   291.5 2066.49  291.88 2076.31   295.8
 2102.47  296.39 2220.22  292.62  2279.1  293.89  2334.7  305.46 2400.12  333.92
#Mann= 3 , 0 , 0
  248.95     .12       0 1932.39    .045       0 2023.97     .12       0
Bank Sta=1932.39,2023.97
XS Rating Curve= 0 ,0
Exp/Cntr=0.3,0.1

Type RM Length L Ch R = 1 ,13923.76,482.49,494.26,505.93
XS GIS Cut Line= 3
2459875.38694679298768.7955180632459802.66692795297873.363822684
2459731.03647428296991.350844748
#Sta/Elev= 30
  101.64  359.01   170.5   306.3  196.73  306.25  206.56  293.07   216.4  290.29
  744.28  289.49   832.8  295.44  855.76  292.23  878.71  295.69  921.33  295.08
  950.84  301.14 1052.46  298.97 1081.96  294.26 1140.95  298.14 1249.11  298.52
 1294.99  294.43 1422.81  295.48 1451.51  291.51 1451.51  287.51 1451.51  282.51
 1551.51  282.51 1551.51  287.51 1551.51  287.52 1563.74  287.54 1606.35  299.44
 1675.18  289.63 1707.95   293.2 1806.28  321.77 1865.27  350.55 1884.93   364.4
#Mann= 3 , 0 , 0
  101.64     .12       0 1451.51    .035       0 1551.51     .12       0
Bank Sta=1451.51,1551.51
XS Rating Curve= 0 ,0
Exp/Cntr=0.3,0.1

Type RM Length L Ch R = 1 ,13429.5 ,499.18,505.46,511.73
XS GIS Cut Line= 3
2460058.73993413298655.1921217292460176.42044553 297893.76798135
2460278.06500526297236.100566029
#Sta/Elev= 30
   229.5  333.15  242.61  326.97  268.84  305.16  285.24  304.75  298.35  290.35
  304.91  289.05  803.25  288.36  816.36  288.67  842.59  294.39   872.1  291.67
  937.67  295.61  990.13  293.67 1003.24  291.51 1019.63  294.22 1049.14  293.74
 1062.25  297.23 1088.48  300.06 1170.43  295.44 1229.44  295.63 1298.29  298.72
  1386.8  291.44 1413.03  286.16 1436.22  286.21 1436.22  281.38 1536.22  281.38
 1536.22  286.38 1536.22   286.8 1547.44  287.37 1573.66  293.74 1665.45  333.22
#Mann= 3 , 0 , 0
   229.5     .12       0 1436.22    .035       0 1536.22     .12       0
Bank Sta=1436.22,1536.22
XS Rating Curve= 0 ,0
Exp/Cntr=0.3,0.1

Type RM Length L Ch R = 1 ,12924.04,376.92,380.11,383.31
XS GIS Cut Line= 3
2460359.81049868298859.5511547772460647.53498887297853.948835269
2460922.57741778296892.671230271
#Sta/Elev= 30
       0  485.29   26.23   480.6   52.46  471.33   91.81  451.78   170.5  403.36
   295.1  307.22  314.77  303.74     341  288.16 1101.68  284.41 1157.41  297.32
 1213.14  290.86 1242.65  296.94  1295.1  298.09 1331.16  287.41 1347.55   288.7
  1361.7  284.02  1361.7  279.11  1461.7  279.11  1461.7  284.11  1461.7  284.31
 1495.07  290.21 1573.75  329.12 1639.31  368.64 1658.98  389.87 1724.54  418.31
  1760.6  438.09 1819.61   476.5 1872.06  500.11 1908.12  511.31 2045.81  536.21
#Mann= 3 , 0 , 0
       0     .12       0  1361.7    .035       0  1461.7     .12       0
Bank Sta=1361.7,1461.7
XS Rating Curve= 0 ,0
Exp/Cntr=0.3,0.1

Type RM Length L Ch R = 1 ,12543.93,597.27,656.78,714.79
XS GIS Cut Line= 3
2460704.84139671298747.9987298092461015.84888478297874.845775098
2461208.14307343 297334.98069087
#Sta/Elev= 30
  164.71  371.67  171.26  368.64  197.46  348.17  207.29  337.46  253.14  303.92
  276.07  302.65  289.17  289.47  308.82  289.55  318.65  286.76  970.41  282.23
 1022.82  285.79 1071.95  283.02 1088.32  284.07 1114.52  293.34 1173.47  297.93
 1232.41  297.15 1261.89  292.88 1288.08  295.69 1314.28  291.81 1349.74  281.14
 1349.74  281.11 1349.74  276.11 1449.74  276.11 1449.74  281.11 1449.74  284.91
 1461.65  290.27 1484.57   294.6 1589.36  327.01 1618.84  342.11 1664.68  371.94
#Mann= 3 , 0 , 0
  164.71     .12       0 1349.74    .035       0 1449.74     .12       0
Bank Sta=1349.74,1449.74
XS Rating Curve= 0 ,0
Exp/Cntr=0.3,0.1

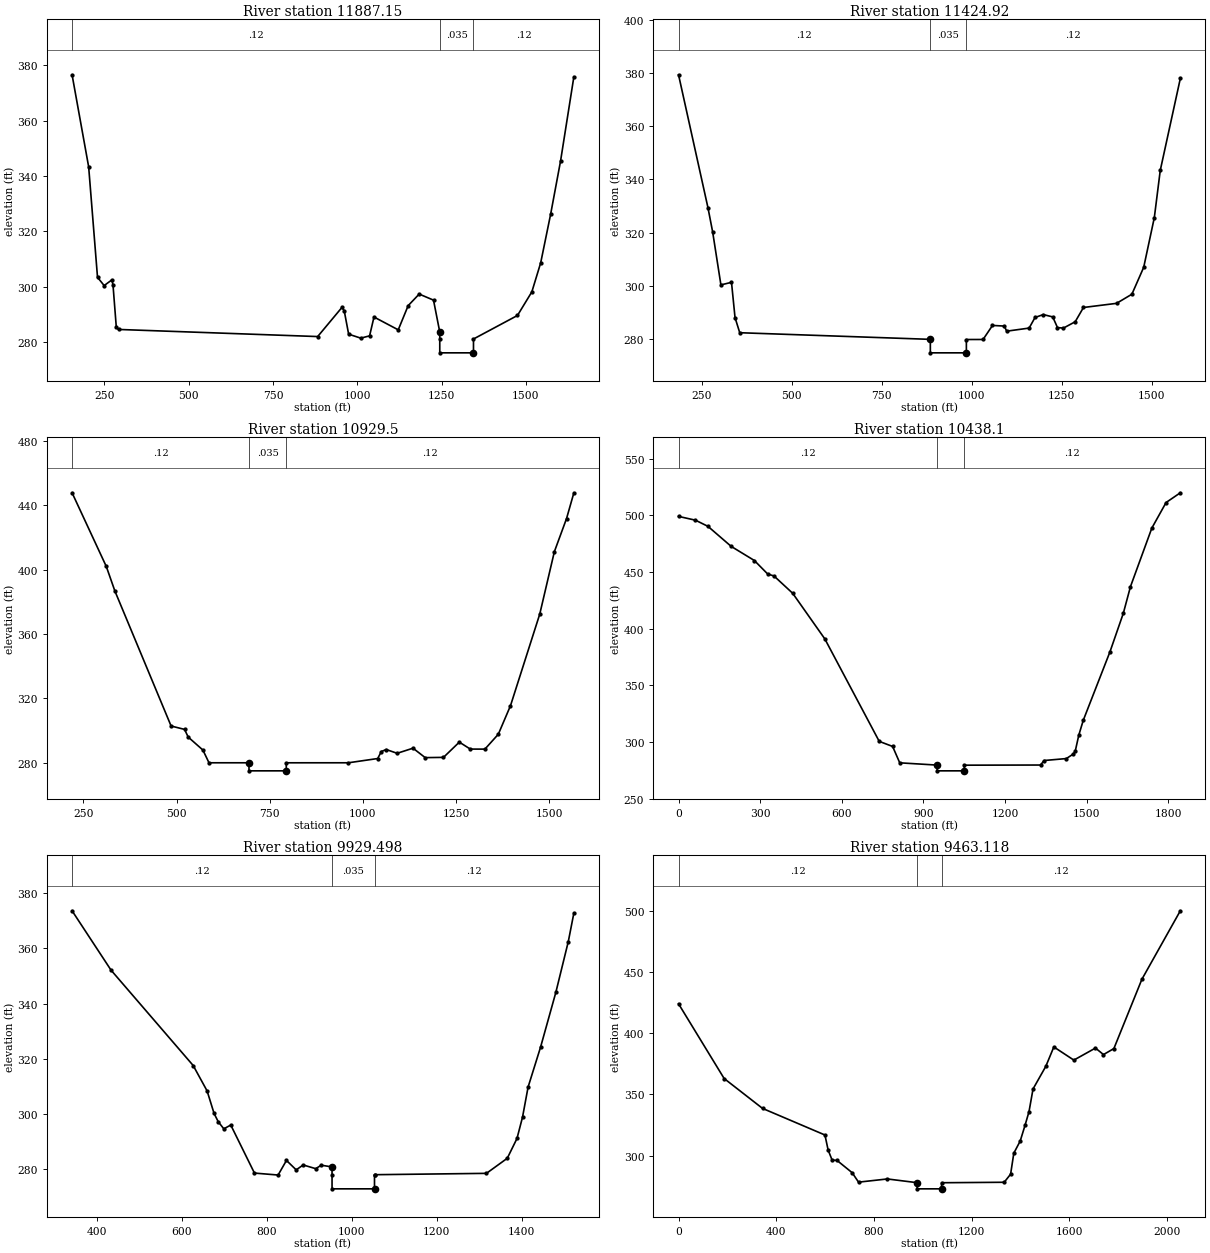
Type RM Length L Ch R = 1 ,11887.15,461.51,462.24,462.87
XS GIS Cut Line= 4
2460762.36028748298785.8641385142461139.11044927298057.421853527
2461475.22755919298038.5803557632461805.90019078298020.043915795
#Sta/Elev= 30
  154.18  376.52  203.39  343.25  229.63  303.35  249.31  300.37  272.27  302.43
  275.55  300.59   285.4  285.23  291.96  284.52  882.43  281.95   954.6   292.5
  961.16  291.29  974.29  282.81 1010.24  281.38 1036.38   282.2 1049.46  289.01
 1121.36  284.38 1150.78  293.12 1183.46   297.3 1225.95  295.11 1244.49  283.59
 1244.49  281.07 1244.49  276.07 1344.49  276.07 1344.49  281.07 1474.88  289.57
 1517.51  298.09 1543.74  308.58 1573.25  326.15 1602.76  345.43 1642.11  375.78
#Mann= 3 , 0 , 0
  154.18     .12       0 1244.49    .035       0 1344.49     .12       0
Bank Sta=1244.49,1344.49
XS Rating Curve= 0 ,0
Exp/Cntr=0.3,0.1

Type RM Length L Ch R = 1 ,11424.92,514.76,495.42,475.69
XS GIS Cut Line= 4
2460850.08110829298872.1090007792461097.26768519298510.837285265
2461402.75395086298497.4422989342462051.31782329298469.003702475
#Sta/Elev= 30
  186.21  379.29  267.87  329.41  280.94  320.28  303.81  300.44  333.21   301.4
  343.01  288.17  356.08  282.49  885.08     280  885.08  279.94  885.08  274.94
  985.08  274.94  985.08  279.94 1031.37  279.95  1057.6  285.22 1090.39  284.99
 1096.94  283.07 1159.24  284.23 1175.63  288.21 1198.58   289.3 1224.81  288.42
 1237.93  284.43 1254.32  284.22 1287.11   286.6 1310.06  291.96 1401.86  293.51
 1444.48  296.94 1477.27  307.04 1506.78  325.72 1523.17  343.38 1578.91  377.91
#Mann= 3 , 0 , 0
  186.21     .12       0  885.08    .035       0  985.08     .12       0
Bank Sta=885.08,985.08
XS Rating Curve= 0 ,0
Exp/Cntr=0.3,0.1

Type RM Length L Ch R = 1 ,10929.5 ,486.27,491.4,496.51
XS GIS Cut Line= 3
2460942.44029895299205.4338169282461650.33810136298876.549808443
2462163.16605647298638.294057888
#Sta/Elev= 30
  219.74   447.8  311.57  401.98  334.53  386.76  485.39   302.8  521.47  300.69
  531.31  295.91  570.67  287.86  587.06  279.94  694.33  279.94  694.33  279.93
  694.33  274.93  794.33  274.93  794.33  279.93  960.95  279.94 1039.53  282.58
 1049.33  286.94 1062.41  288.18 1091.82  285.84 1134.32  289.01    1167  283.14
 1216.03   283.3 1258.52  292.78 1287.94  288.46 1327.16  288.43 1363.12  297.68
  1395.8  315.44 1474.25  372.35 1513.47  411.17 1546.16  431.78 1565.77  447.75
#Mann= 3 , 0 , 0
  219.74     .12       0  694.33    .035       0  794.33     .12       0
Bank Sta=694.33,794.33
XS Rating Curve= 0 ,0
Exp/Cntr=0.3,0.1

Type RM Length L Ch R = 1 ,10438.1 ,522.83,508.6,493.89
XS GIS Cut Line= 3
 2460642.2646582299769.7192819422461587.26408052299443.555892274
2462385.25756328299168.131574348
#Sta/Elev= 30
       0  499.03   62.28  495.67  108.16  490.23  193.39  472.57  278.61   460.1
  327.77  448.15  350.72  446.45  419.55  431.15  537.55  390.91  737.49  300.48
  786.65     296  812.87  281.54  950.18  279.54  950.18  279.47  950.18  274.47
 1050.18  274.47 1050.18  279.46 1330.18   279.6 1343.26  283.58 1425.07   285.3
 1451.24   289.4 1457.79   291.9 1470.87  306.05 1487.23  319.07 1585.39  379.55
 1634.47  413.57 1660.65  437.03 1739.18  488.71 1791.53  511.28 1843.88  519.87
#Mann= 3 , 0 , 0
       0     .12       0  950.18    .035       0 1050.18     .12       0
Bank Sta=950.18,1050.18
XS Rating Curve= 0 ,0
Exp/Cntr=0.3,0.1

Type RM Length L Ch R = 1 ,9929.498,471.36,466.38,461.33
XS GIS Cut Line= 3
2461272.62091179300273.4638405822461810.85024753 299887.49693352
2462233.02215584299584.755677563
#Sta/Elev= 30
  340.99  373.65   432.8  352.14  626.25   317.6  659.03  308.39  675.43  300.25
  685.26  297.23  698.38  294.67  714.77  296.04  770.51  278.64  826.25  277.93
  845.92  283.22  868.87   279.8  885.27  281.58  914.78  280.24  927.89  281.49
  953.28  280.87  953.28  277.93  953.28  272.93 1053.28  272.93 1053.28  277.93
 1053.28  278.05 1316.97  278.54 1365.98     284 1388.85  291.17 1401.92  298.91
 1414.99  309.78 1444.39  324.25 1480.33  344.07 1509.74  362.51 1522.81  372.81
#Mann= 3 , 0 , 0
  340.99     .12       0  953.28    .035       0 1053.28     .12       0
Bank Sta=953.28,1053.28
XS Rating Curve= 0 ,0
Exp/Cntr=0.3,0.1

Type RM Length L Ch R = 1 ,9463.118,557.16,533.62,509.44
XS GIS Cut Line= 3
 2461328.5034432300929.6651247742462078.07149786300269.047351524
2462869.91243386 299571.17407535
#Sta/Elev= 30
       0  424.11  186.72  363.02  343.96  338.58  599.48  316.84  612.58  304.51
  628.96  296.29  648.62   296.1  710.86  286.03  737.07  278.29     855   280.9
  977.07  277.85  977.07  277.82  977.07  272.82 1077.07  272.82 1077.07  277.81
 1333.48  278.19 1359.71  284.81 1372.82  301.98 1399.04  311.92 1418.71  324.73
  1435.1  335.98 1451.49  354.46 1503.94  373.01 1536.72  388.84 1618.66  378.07
 1707.17  387.92 1739.95  382.59 1782.56   387.5 1897.29  444.17 2054.63  500.16
#Mann= 3 , 0 , 0
       0     .12       0  977.07    .035       0 1077.07     .12       0
Bank Sta=977.07,1077.07
XS Rating Curve= 0 ,0
Exp/Cntr=0.3,0.1

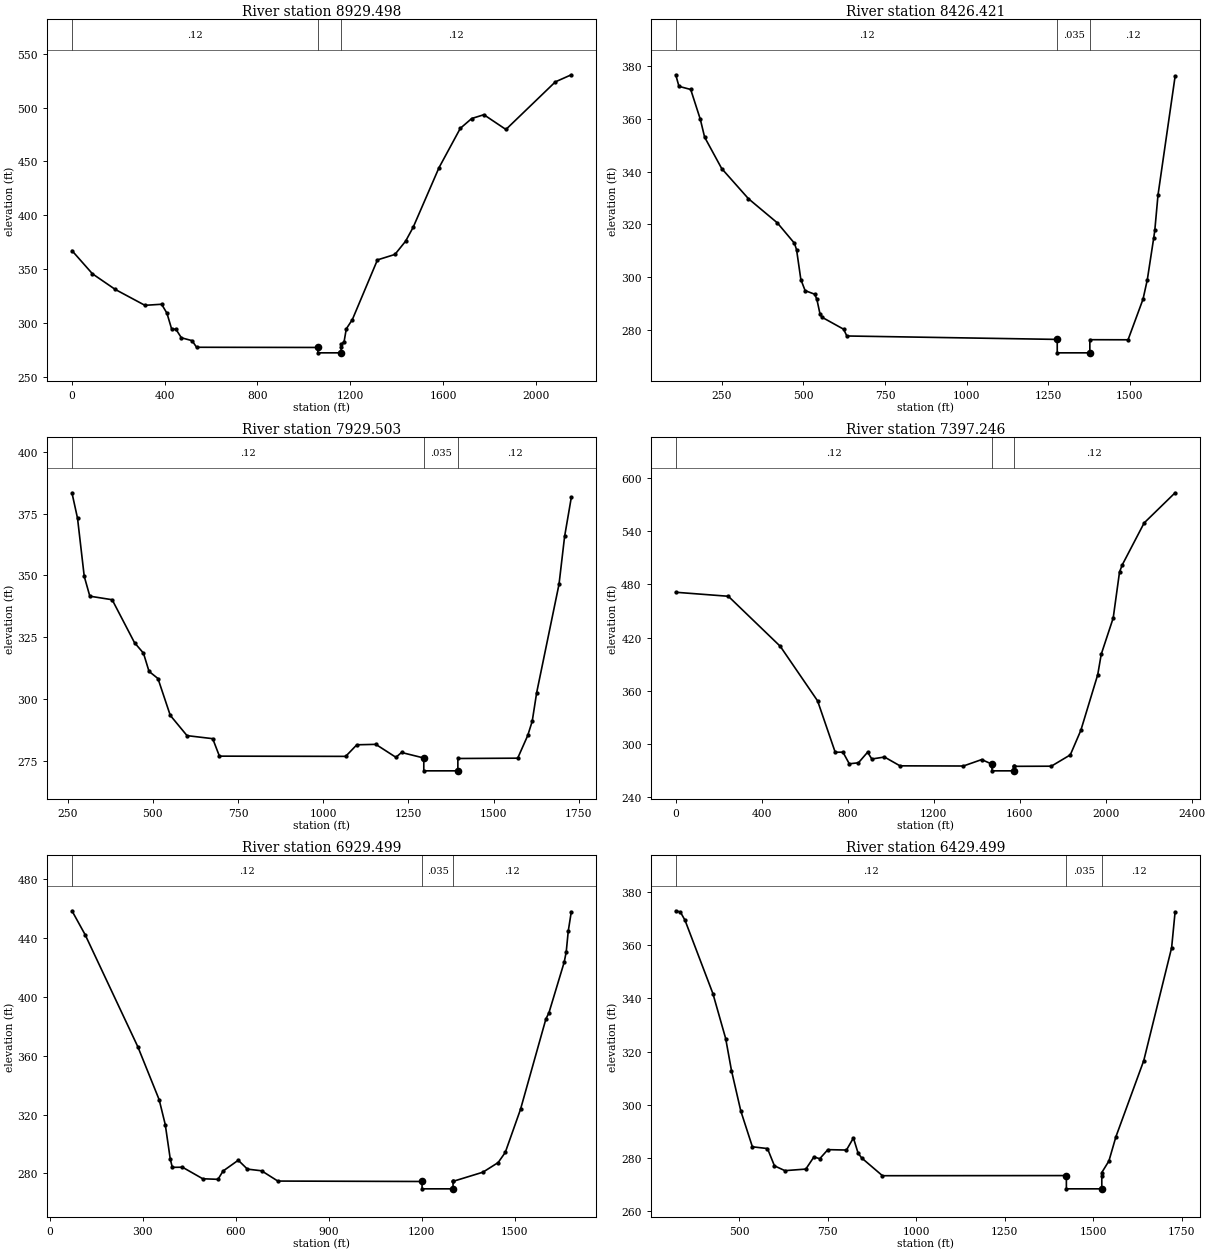
Type RM Length L Ch R = 1 ,8929.498,473.91,503.08,529.62
XS GIS Cut Line= 5
2461789.22069761301175.4900924412462562.47866553300506.471417353
2462594.41036019300424.5778803532462621.90768053300354.057352111
2463358.66506527299727.573368847
#Sta/Elev= 30
       0  367.41   88.49  345.86   186.8  331.39  314.62  316.67  386.72  317.66
  409.66  309.32  429.32   295.1  448.98  294.26  471.92  286.57  517.81  283.93
  537.47  277.78 1060.44   277.6 1060.44  272.62 1160.44  272.62 1160.44  277.62
 1160.44  280.47 1173.48  282.99 1182.94  294.85 1209.05  303.44 1317.23  358.77
 1392.63  363.84 1438.53  376.09 1471.31  389.02 1582.77   444.3 1674.56  480.75
 1723.74  489.85 1776.19  493.37 1871.26  479.69 2084.35  523.82 2153.19  530.39
#Mann= 3 , 0 , 0
       0     .12       0 1060.44    .035       0 1160.44     .12       0
Bank Sta=1060.44,1160.44
XS Rating Curve= 0 ,0
Exp/Cntr=0.3,0.1

Type RM Length L Ch R = 1 ,8426.421,489.93,496.92,503.78
XS GIS Cut Line= 3
2462006.75066593301386.7460451742462741.52030219300825.192236602
2463223.52819765300456.813516811
#Sta/Elev= 30
  108.22  376.63  118.06  372.25  154.13  371.07  183.65  359.75  196.76  353.03
  249.23  341.13  331.22  329.73  419.76   320.6  472.23  312.88  478.79   310.4
  491.91  299.15  505.02  294.95  534.54  293.59   541.1  291.61  550.94  285.97
  557.49  284.83  623.08  280.35  632.92  277.79 1278.18  276.49 1278.18  276.41
 1278.18  271.41 1378.18  271.41 1378.18  276.38 1495.38  276.35 1541.29  291.72
  1554.4  299.06 1574.08  314.89 1577.36  317.71  1587.2  331.12 1639.66  376.02
#Mann= 3 , 0 , 0
  108.22     .12       0 1278.18    .035       0 1378.18     .12       0
Bank Sta=1278.18,1378.18
XS Rating Curve= 0 ,0
Exp/Cntr=0.3,0.1

Type RM Length L Ch R = 1 ,7929.503,536.34,532.26,525.07
XS GIS Cut Line= 3
2462315.87502149301585.6491247622462958.11501336301222.586783022
2463591.75046139300864.417431715
#Sta/Elev= 30
  262.32  383.47  278.71  373.14  298.38  349.63  314.78  341.59  380.36  340.15
  445.94  322.76  472.17  318.52  488.56  311.13  514.79  308.23  550.86  293.33
  600.05  285.11  675.46  283.88  695.14   276.8 1065.65  276.71 1098.44   281.4
 1154.18  281.58 1213.19  276.33 1229.58  278.29 1294.98  276.05 1294.98  275.85
 1294.98  270.85 1394.98  270.85 1394.98  275.85 1570.57  275.98 1600.07  285.17
 1613.19  290.93  1626.3  302.54 1691.88  346.43 1708.27  365.78 1727.94  381.59
#Mann= 3 , 0 , 0
  262.32     .12       0 1294.98    .035       0 1394.98     .12       0
Bank Sta=1294.98,1394.98
XS Rating Curve= 0 ,0
Exp/Cntr=0.3,0.1

Type RM Length L Ch R = 1 ,7397.246,476.79,467.75,458.63
XS GIS Cut Line= 4
2462200.87833886302161.8995369372462627.88765544302149.447134018
2463350.71691844301628.6492910982464165.60472436301041.523496851
#Sta/Elev= 30
       0  470.93  244.57  466.42  486.15  410.08  659.74  348.66  741.63  290.85
  777.66  290.92  807.14  277.84  849.72  278.96   892.3  290.89  911.95  283.23
   970.9  285.45 1042.96  275.53 1337.72  275.34 1422.78  282.56 1470.88  277.41
 1470.88   274.9 1470.88   269.9 1570.88   269.9 1570.88   274.9 1570.88  274.98
 1746.67  275.13    1835  287.85 1884.07   315.5 1962.59  378.11 1978.94  401.17
 2034.56  441.94    2064  493.79 2077.09  501.95 2178.51  548.98 2322.46  582.92
#Mann= 3 , 0 , 0
       0     .12       0 1470.88    .035       0 1570.88     .12       0
Bank Sta=1470.88,1570.88
XS Rating Curve= 0 ,0
Exp/Cntr=0.3,0.1

Type RM Length L Ch R = 1 ,6929.499,500.8,500,499.16
XS GIS Cut Line= 3
2463037.67069531302681.0885869452463680.85470961302010.323396519
2464152.84341023301518.095050898
#Sta/Elev= 30
   71.99  458.35  114.53  442.11  284.68  365.97   353.4  330.08  373.03  313.23
  389.39  289.57  395.94  284.15  428.66  284.24   494.1   276.4  543.19  276.02
  559.55  281.64  608.63  288.98  638.08  282.95  683.89  281.81  736.25  274.84
 1201.68  274.55 1201.68  269.56 1301.68  269.56 1301.68  274.56 1301.68  274.64
 1398.01  280.86 1447.19  287.39 1470.14  294.28 1519.32  323.52 1601.29  384.91
 1611.12  389.12  1660.3  423.45 1666.86  430.47 1673.41  444.59 1683.25  457.69
#Mann= 3 , 0 , 0
   71.99     .12       0 1201.68    .035       0 1301.68     .12       0
Bank Sta=1201.68,1301.68
XS Rating Curve= 0 ,0
Exp/Cntr=0.3,0.1

Type RM Length L Ch R = 1 ,6429.499,507.94,500,492.05
XS GIS Cut Line= 3
2463430.17791519303020.8389475232463891.84936635  302523.3660056
2464389.19984827301987.448208161
#Sta/Elev= 30
  321.31  372.87  334.43   372.4  347.54  369.29  426.23  341.77   462.3  324.88
  478.69  312.86  504.92  297.72  537.71  284.23  580.33  283.57     600  277.08
  629.51  275.27  688.53  275.86  711.48  280.43  727.87  279.75  750.82  283.16
  803.28  283.01  822.95  287.55  836.07  281.89   845.9  280.08  904.92  273.37
 1424.19  273.42 1424.19  268.44 1524.19  268.44 1524.19  273.44 1524.19  274.57
 1544.27   278.9 1563.94  287.96 1642.63  316.59 1721.32  358.99 1731.15  372.47
#Mann= 3 , 0 , 0
  321.31     .12       0 1424.19    .035       0 1524.19     .12       0
Bank Sta=1424.19,1524.19
XS Rating Curve= 0 ,0
Exp/Cntr=0.3,0.1

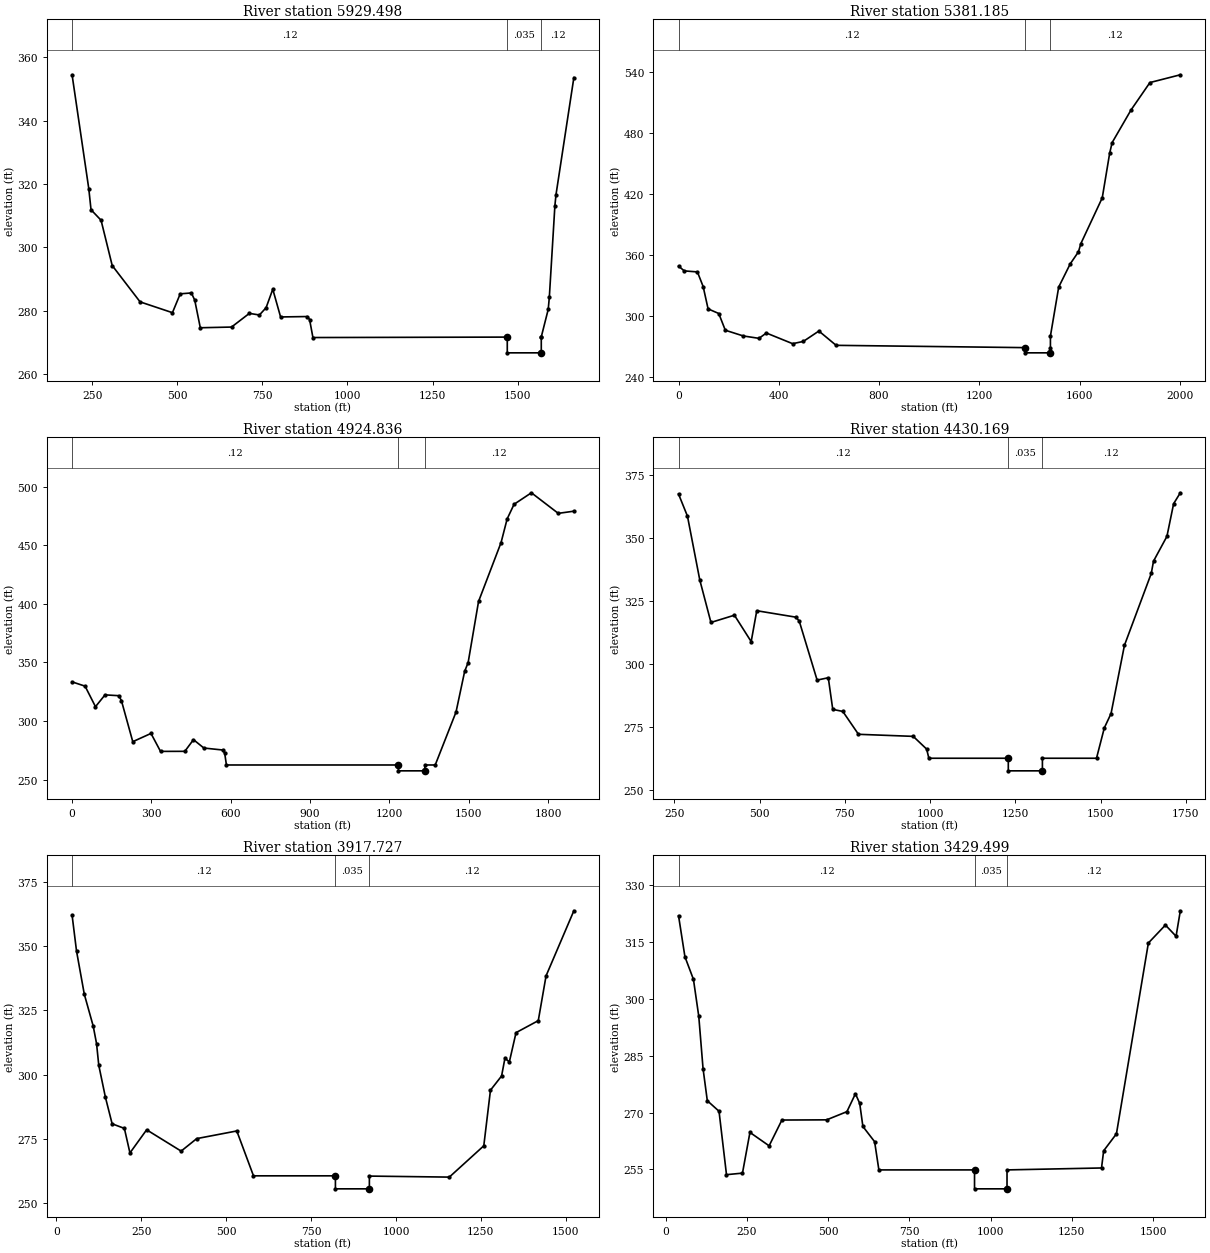
Type RM Length L Ch R = 1 ,5929.498,547.21,548.31,549.33
XS GIS Cut Line= 3
2463872.86065952303583.2340261232464322.85309753 302909.92363143
2464692.68168021302356.561244415
#Sta/Elev= 30
  190.16  354.51  239.34  318.52   245.9   311.9  275.41  308.58   308.2  294.28
  390.16  282.81  485.25   279.4   508.2  285.35  540.98  285.63  550.82  283.36
  567.21  274.64  659.02  274.86  711.48  279.18  740.98  278.67  760.66  280.97
  780.33   286.8  803.28  278.05  881.97  278.18  888.52  277.23  898.36  271.55
 1469.79  271.69 1469.79  266.72 1569.79  266.72 1569.79  271.72 1569.79  271.76
 1590.17  280.43 1593.45  284.26 1609.84  313.23 1613.12   316.7 1665.58  353.61
#Mann= 3 , 0 , 0
  190.16     .12       0 1469.79    .035       0 1569.79     .12       0
Bank Sta=1469.79,1569.79
XS Rating Curve= 0 ,0
Exp/Cntr=0.3,0.1

Type RM Length L Ch R = 1 ,5381.185,438.62,456.35,469.33
XS GIS Cut Line= 3
2464258.09371261303935.9566843512464832.83698569303115.156488687
2465406.41129786302296.025252938
#Sta/Elev= 30
       0  349.22   22.92  344.49   75.32  343.48   98.24  329.12  117.88  307.25
  160.45   302.7  186.65  286.29  258.69  280.66  320.91  278.34  350.38  283.56
  455.17  273.11  497.73  275.29  559.95   285.5  628.72  271.48 1383.73  269.22
 1383.73  269.12 1383.73  264.12 1483.73  264.12 1483.73  269.12 1483.73  280.56
 1516.77  328.64 1562.67  351.35 1595.46  363.17  1605.3  371.33 1690.54  416.17
 1720.05  459.85 1729.89   470.3 1805.29  502.31  1880.7  529.21 2002.01  536.84
#Mann= 3 , 0 , 0
       0     .12       0 1383.73    .035       0 1483.73     .12       0
Bank Sta=1383.73,1483.73
XS Rating Curve= 0 ,0
Exp/Cntr=0.3,0.1

Type RM Length L Ch R = 1 ,4924.836,513.36,494.67,480.58
XS GIS Cut Line= 5
2464573.29911894304065.0082635132465287.89086561303162.489727348
2465397.27680169303086.6283305142465457.90430512303035.539521933
2465793.14871337302619.695537359
#Sta/Elev= 30
       0  333.45   49.19  329.78   88.55  312.25  124.63  322.34   177.1  321.64
  186.94   317.2  229.58  282.37  298.45  289.41  334.53  274.08  426.36  274.13
  459.15  284.09  498.51  276.94  570.66  275.24  577.22  272.49  583.78  262.47
 1234.32  262.47 1234.32  257.47 1334.32  257.47 1334.32  262.47  1373.4  262.47
 1452.04  307.66 1484.81  342.51 1497.92  349.94 1537.25  402.11 1622.45  452.43
 1645.39  472.59  1671.6   485.1 1737.14  494.92 1838.73  477.35 1897.71   479.2
#Mann= 3 , 0 , 0
       0     .12       0 1234.32    .035       0 1334.32     .12       0
Bank Sta=1234.32,1334.32
XS Rating Curve= 0 ,0
Exp/Cntr=0.3,0.1

Type RM Length L Ch R = 1 ,4430.169,532.18,512.44,492.49
XS GIS Cut Line= 3
2465180.66372231304279.3715439732465591.39747643303666.990030691
2466000.30353297 303057.33308851
#Sta/Elev= 30
  262.18   367.4  288.39  358.59  324.44   333.3  357.22   316.4  426.04  319.28
   475.2   308.8  491.58  321.06  606.28   318.5  616.12  316.95  668.55  293.51
  701.32  294.44  714.43  281.88  743.93  281.06  789.81  271.98  950.39  271.16
  989.71  266.11  996.27  262.47  1229.2  262.47  1229.2  257.47  1329.2  257.47
  1329.2  262.47 1487.84  262.47 1510.78  274.54 1530.45  280.21 1569.77  307.33
 1648.43  335.87 1654.98  340.74 1694.31  350.58 1713.97  363.56 1733.63   367.9
#Mann= 3 , 0 , 0
  262.18     .12       0  1229.2    .035       0  1329.2     .12       0
Bank Sta=1229.2,1329.2
XS Rating Curve= 0 ,0
Exp/Cntr=0.3,0.1

Type RM Length L Ch R = 1 ,3917.727,497.19,488.23,479.22
XS GIS Cut Line= 3
2466040.89099275304442.1019179212466224.71084236303505.903738692
2466325.68759877302991.628056867
#Sta/Elev= 30
    45.9  362.28   59.01  348.22   81.96  331.34  108.19   318.9  118.03  312.05
  124.59  303.58  144.26  291.04  163.93  280.75  199.99  278.96  216.39  269.38
  265.57  278.41   367.2  270.09   413.1  274.97  531.13  277.96  580.31  260.44
  821.68  260.44  821.68  260.36  821.68  255.36  921.68  255.36  921.68  260.34
  1157.2  259.94 1258.74  272.16 1278.39  293.87 1311.15  299.42 1320.97  306.31
 1334.08  304.96 1353.73  316.35 1419.24  321.03 1442.17  338.52 1524.06  363.93
#Mann= 3 , 0 , 0
    45.9     .12       0  821.68    .035       0  921.68     .12       0
Bank Sta=821.68,921.68
XS Rating Curve= 0 ,0
Exp/Cntr=0.3,0.1

Type RM Length L Ch R = 1 ,3429.499,497.11,500,502.88
XS GIS Cut Line= 3
2466672.97205906304582.1647329212466687.15676786303621.094453186
2466695.76774639303037.666337085
#Sta/Elev= 30
   39.37  322.01   59.05  311.17   85.29  305.19  101.69  295.42  114.82  281.63
  127.94  273.15  164.02  270.37  186.99  253.62  236.19  254.03  259.16  264.78
  318.21  261.24  357.57  268.05  495.35   268.1  557.68  270.26  583.92  274.99
  597.05  272.46  606.89  266.35  642.97  262.33  656.09  254.88  950.53  254.88
  950.53  249.88 1050.53  249.88 1050.53  254.88 1341.46  255.39 1348.02  259.93
 1387.36  264.41  1485.7   314.8 1538.15  319.54 1570.93  316.58 1584.04  323.31
#Mann= 3 , 0 , 0
   39.37     .12       0  950.53    .035       0 1050.53     .12       0
Bank Sta=950.53,1050.53
XS Rating Curve= 0 ,0
Exp/Cntr=0.3,0.1

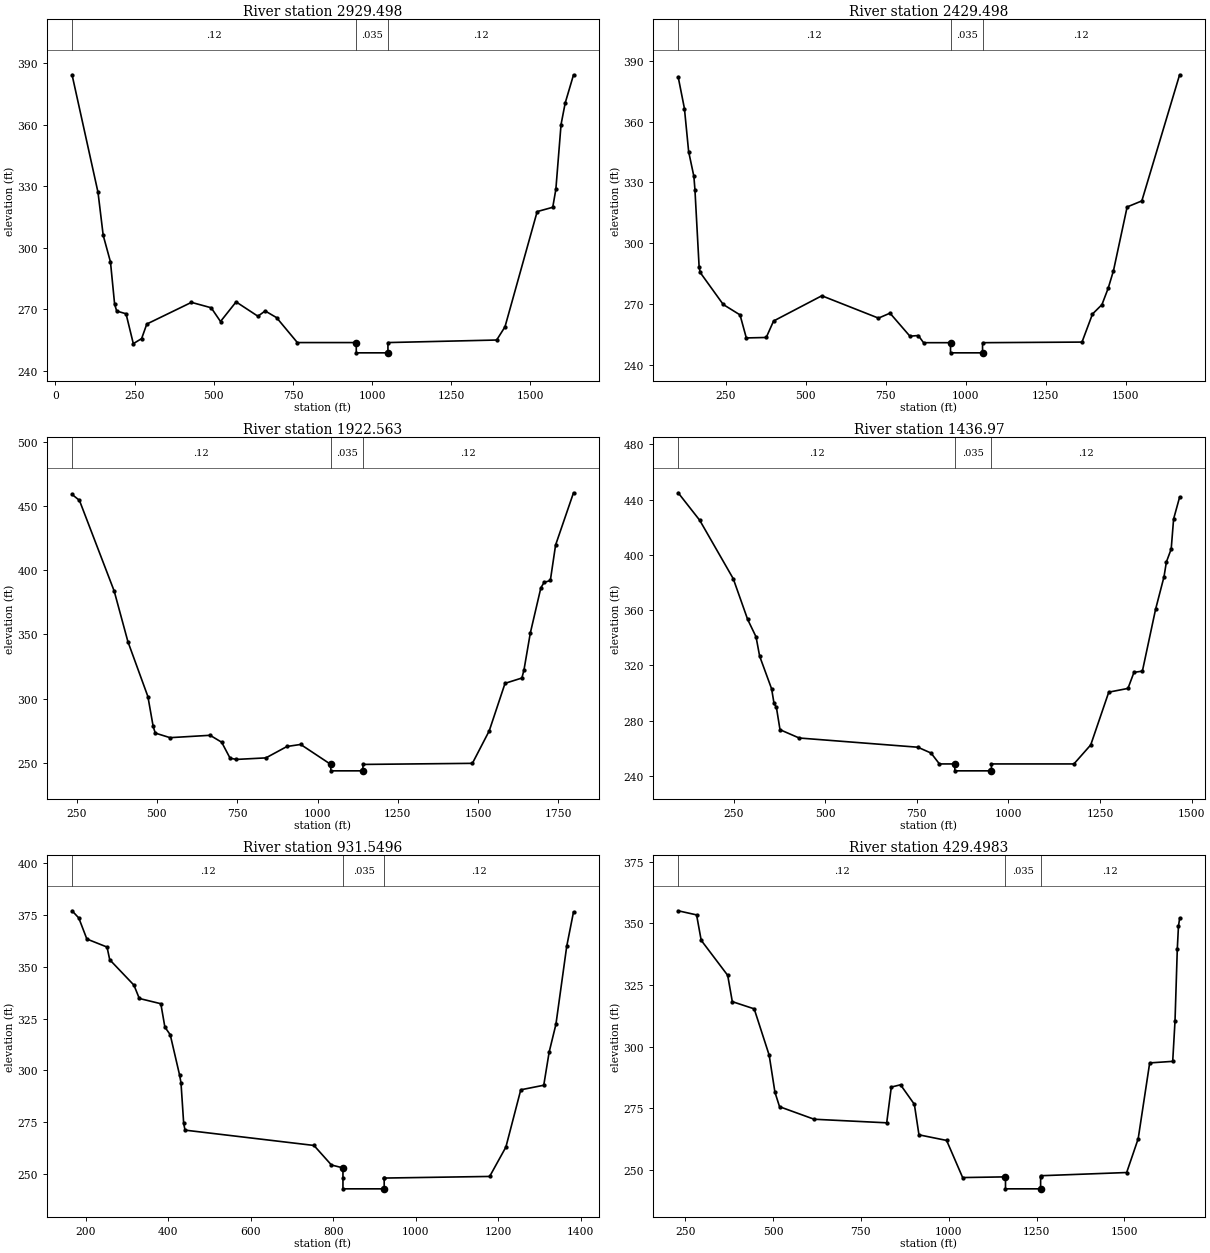
Type RM Length L Ch R = 1 ,2929.498,495.77,500,504.22
XS GIS Cut Line= 3
2467115.92283086304614.4464470342467184.50058945303669.391600683
2467230.53206958303035.043037642
#Sta/Elev= 30
   52.46  384.23  134.43     327  150.82  306.07  173.77  293.13  186.89  272.55
  193.44  269.21  222.95  267.89   245.9  253.34  272.13   255.8  288.52  262.89
  429.51  273.44   491.8  270.81  521.31  264.12  570.49  273.67  639.34   266.7
   662.3  269.26  698.36  266.01  763.94  253.87     950  253.87     950  248.87
    1050  248.87    1050  253.87 1393.41  255.11 1419.64  261.54 1521.27  317.63
 1570.45  319.73 1580.28  328.47 1596.67  360.01 1609.79  370.51 1636.02  384.17
#Mann= 3 , 0 , 0
   52.46     .12       0     950    .035       0    1050     .12       0
Bank Sta=950,1050
XS Rating Curve= 0 ,0
Exp/Cntr=0.3,0.1

Type RM Length L Ch R = 1 ,2429.498,505.3,506.94,508.55
XS GIS Cut Line= 3
2467542.12299488304597.2433118162467682.89460577 303707.59231168
2467786.89047628303050.357311322
#Sta/Elev= 30
  101.54  382.05  121.19  366.37  134.29  345.22  150.67  332.96  153.94   326.5
  167.04  288.35  170.32  285.66  242.38  269.88  294.78  264.76  314.43  253.41
  376.67  253.64  399.59  261.75  550.26  274.18  727.13  263.17  763.16  265.61
  825.39  254.27  851.59   254.6  867.97  251.07  952.23  251.07  952.23  246.07
 1052.23  246.07 1052.23  251.07 1362.83  251.37 1395.61   265.2 1425.11  269.81
 1444.78  277.96 1461.17  286.56 1503.79  317.93 1549.68   320.9 1667.68  383.03
#Mann= 3 , 0 , 0
  101.54     .12       0  952.23    .035       0 1052.23     .12       0
Bank Sta=952.23,1052.23
XS Rating Curve= 0 ,0
Exp/Cntr=0.3,0.1

Type RM Length L Ch R = 1 ,1922.563,477.25,485.59,493.86
XS GIS Cut Line= 3
2468018.68859502304647.8428573282468162.58065428303897.484976515
2468312.61930081303115.073576872
#Sta/Elev= 30
  236.09  459.17  259.05  454.51  367.26  383.77  409.89  344.37  472.19  301.48
  488.58  278.18  495.14  273.03  541.05  269.46  665.65  271.31  701.72  265.91
  727.96  253.44  747.63   252.5  839.44  253.69  905.03  262.59  947.65  264.17
 1041.46  248.59 1041.46  243.59 1141.46  243.59 1141.46  248.59 1482.05  249.44
  1534.5  274.79 1583.68  311.83 1636.13  315.98 1642.69   322.4 1662.36  351.08
 1695.14  386.28 1704.98   390.5 1724.65  392.04 1741.04  419.72 1796.78  460.44
#Mann= 3 , 0 , 0
  236.09     .12       0 1041.46    .035       0 1141.46     .12       0
Bank Sta=1041.46,1141.46
XS Rating Curve= 0 ,0
Exp/Cntr=0.3,0.1

Type RM Length L Ch R = 1 ,1436.97 ,501.86,505.42,508.83
XS GIS Cut Line= 3
2468372.96301026304662.4074134852468603.02563952304042.907914013
 2468849.5766056303379.010203469
#Sta/Elev= 30
   98.14  444.88  157.03  424.97  248.63  382.64  287.89   353.2  310.79  340.59
   320.6  326.62  353.32  302.92  359.86  292.47   366.4  289.49  376.22  273.37
  428.56  267.36  752.44  260.69  788.49  256.48  811.44  248.59  853.45  248.59
  853.45  243.59  953.45  243.59  953.45  248.59 1178.65  248.59 1224.55  262.37
 1273.73  300.54 1326.19  303.26 1342.58  314.89 1365.54  315.75  1401.6  360.55
 1424.55  384.06 1431.11  394.83 1444.22  404.17 1450.78  425.91 1467.18  441.71
#Mann= 3 , 0 , 0
   98.14     .12       0  853.45    .035       0  953.45     .12       0
Bank Sta=853.45,953.45
XS Rating Curve= 0 ,0
Exp/Cntr=0.3,0.1

Type RM Length L Ch R = 1 ,931.5496,515.1,502.05,488.8
XS GIS Cut Line= 4
2468689.21000651304672.1600459832468891.43713619304589.192910686
2469061.93220203304219.3970623462469305.59891672303681.618726914
#Sta/Elev= 30
  166.38  377.03   182.7  373.56  202.27  363.41  251.21  359.53  257.73  353.42
  316.45  341.16   329.5  334.73   381.7  332.19  391.48  320.95  404.51  317.22
  427.31  297.67  430.57  294.11  437.09  274.53  440.34  271.21  753.08  263.82
  795.45  254.39  823.41     253  823.41  247.89  823.41  242.89  923.41  242.89
  923.41  247.89  923.41  248.09 1179.21  248.87 1218.57  263.04 1254.65  290.66
 1310.41  292.87 1323.53   308.9 1339.93  322.27 1366.17  359.97 1382.57  376.45
#Mann= 3 , 0 , 0
  166.38     .12       0  823.41    .035       0  923.41     .12       0
Bank Sta=823.41,923.41
XS Rating Curve= 0 ,0
Exp/Cntr=0.3,0.1

Type RM Length L Ch R = 1 ,429.4983,169.49,173.69,177.88
XS GIS Cut Line= 4
2468768.52245944304739.8996713142469524.87058061 304533.27701202
2469556.83639595304337.8974815162469628.80637239303898.006337226
#Sta/Elev= 30
  229.64  355.13  282.13  353.46  295.25  343.17  370.71  328.96  383.83   318.3
  446.16  315.38  488.81   296.6  505.21  281.59  518.33  275.72  616.75  270.64
  823.43  269.19  836.55  283.68   862.8   284.6  902.16   276.7  915.29  264.32
  994.02  262.05 1039.67     247 1161.68  247.28 1161.68  242.43 1261.68  242.43
 1261.68  247.43 1261.68  247.74 1506.66  249.04 1539.43  262.71 1572.21  293.47
 1637.76   294.1 1644.31  310.37 1650.87  339.71 1654.14  348.83 1657.42  352.02
#Mann= 3 , 0 , 0
  229.64     .12       0 1161.68    .035       0 1261.68     .12       0
Bank Sta=1161.68,1261.68
XS Rating Curve= 0 ,0
Exp/Cntr=0.3,0.1

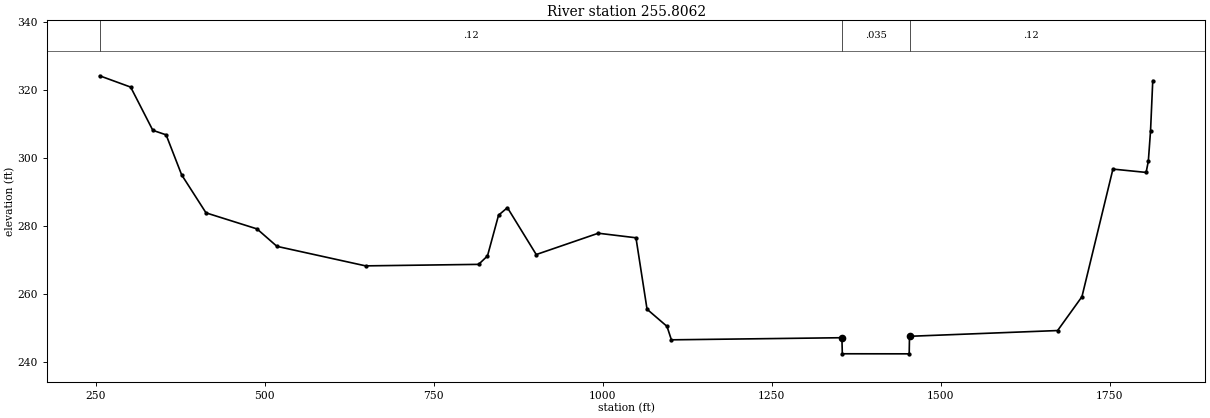
Type RM Length L Ch R = 1 ,255.8062,258.29,255.81,263.11
XS GIS Cut Line= 4
2468825.12274977304809.3953239542469652.45464303304667.927333266
2469723.85115378304383.7008676082469827.53499842 303970.94113849
#Sta/Elev= 30
  255.74  324.13  301.64   320.8  334.43  308.09   354.1  306.76  377.05     295
  413.11  283.82  488.52   279.1  518.03  273.97  649.18  268.23  816.39  268.67
  829.51  271.15   845.9  283.14  859.01  285.34  901.64  271.56  993.44  277.83
 1049.18  276.49 1065.57  255.48 1095.08  250.44 1101.59  246.48 1353.85   247.1
 1354.45  242.38 1453.39  242.36 1453.85  247.52 1672.95  249.21 1708.96  259.16
 1754.79  296.69  1803.9  295.71 1807.17  299.02 1810.44  307.94 1813.72  322.69
#Mann= 3 , 0 , 0
  255.74     .12       0 1353.85    .035       0 1453.85     .12       0
Bank Sta=1353.85,1453.85
XS Rating Curve= 0 ,0
Exp/Cntr=0.3,0.1

Chan Stop Cuts=-1
CM Template=test,False, 0 , 1
 CM Simple Trapezoid=5,100,0,0.035
Use User Specified Reach Order=0
Composite Channel Slope=5

--- Shenandoah2.g01 (geometry) ---

Geom Title=Shenandoah2
Program Version=4.10

River Reach=ShenandoahRiver ,Reach2