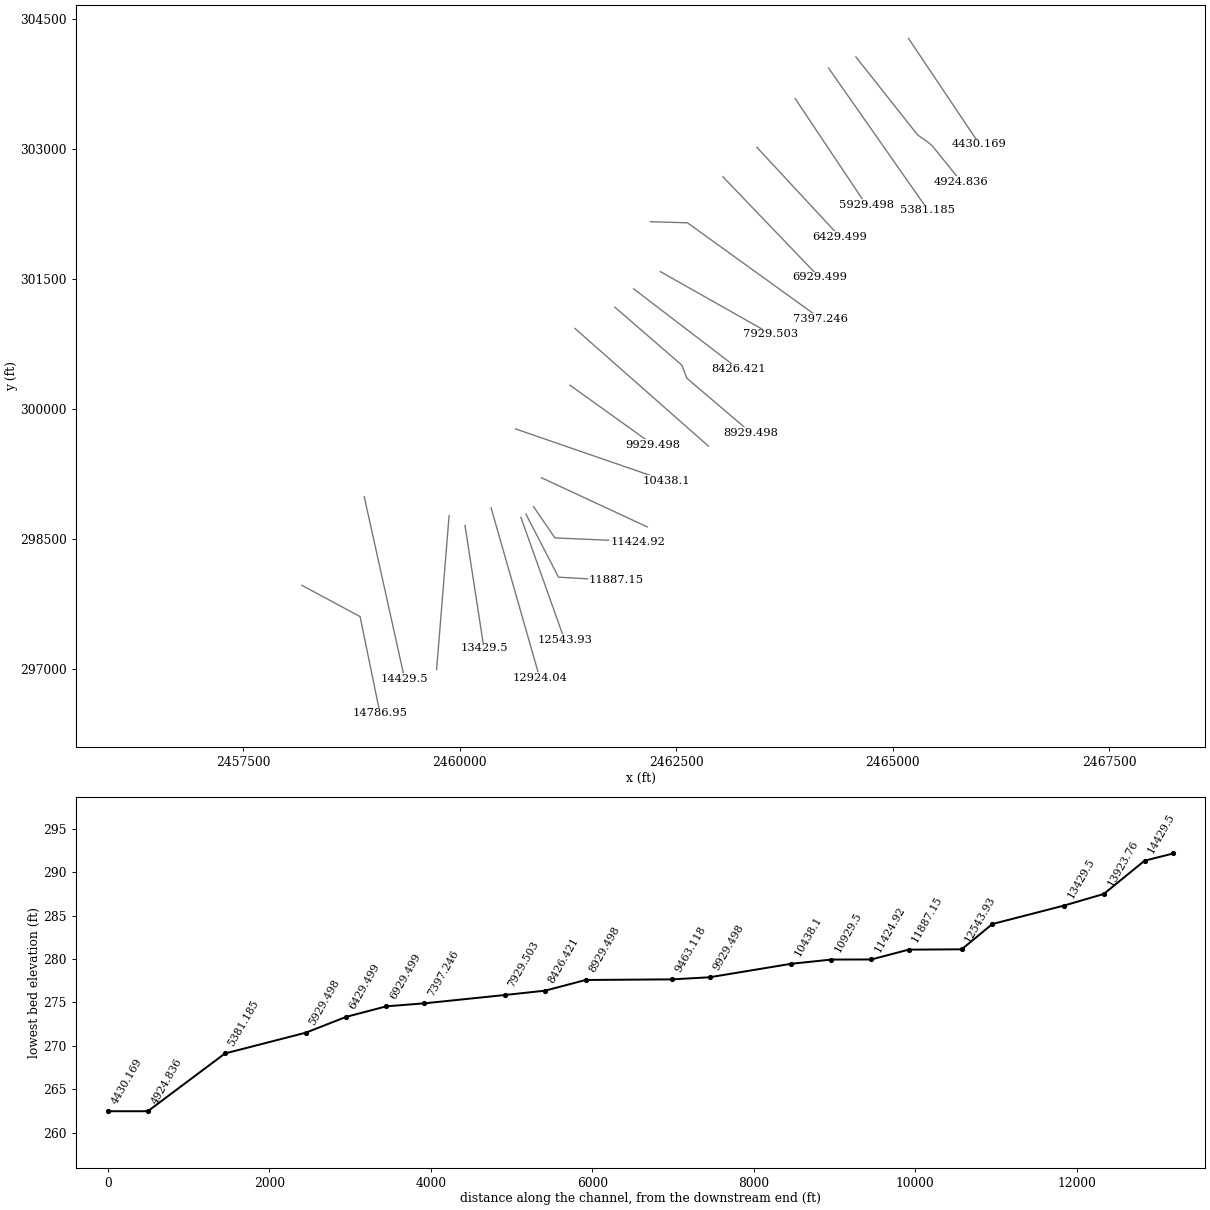
HEC-RAS study Shenandoah2.prj: Shenandoah2

--- Shenandoah2.g01 (geometry) --- (continued)

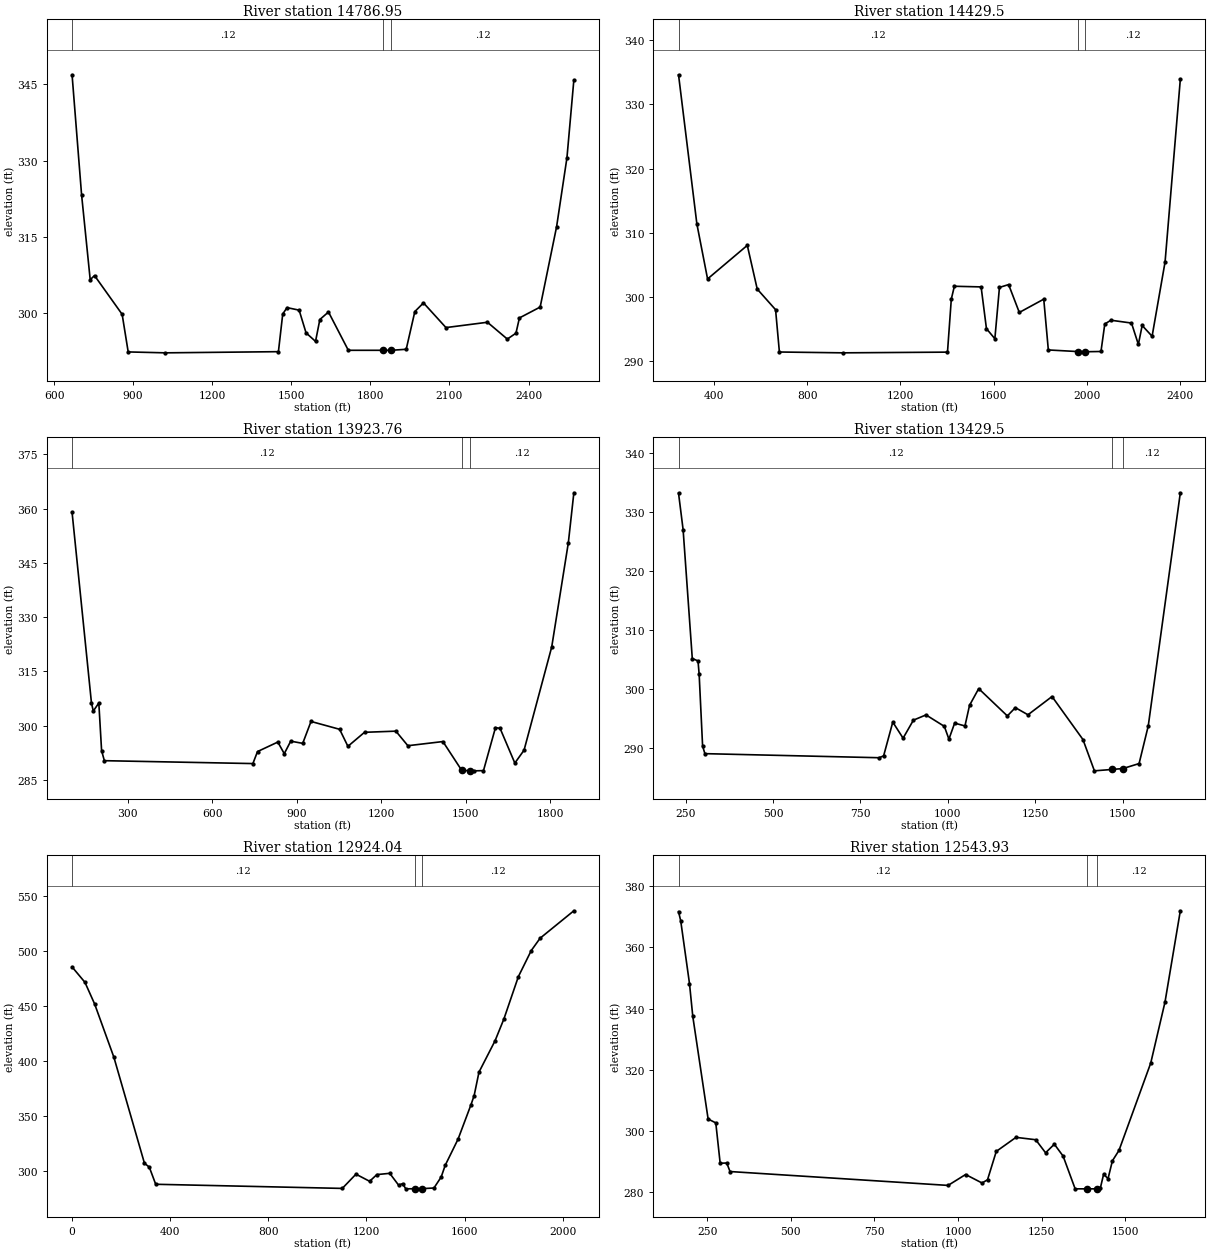
Type RM Length L Ch R = 1 ,14786.95,356.63,357.45,358.22
XS GIS Cut Line= 4
2458175.36619098297963.7467292332458847.45197485297602.020861432
2458916.60111478 297265.247584852459076.84678845296484.810735247
#Sta/Elev= 30
  668.25  346.88  704.28  323.29  737.04  306.55  753.42  307.36  858.24  299.73
  881.17  292.33 1022.03  292.15 1451.14  292.38 1467.51   299.8 1483.88  301.05
 1529.72  300.55 1555.92  296.09 1591.94   294.4 1608.31  298.71 1641.05  300.19
 1716.36  292.65 1848.34  292.65 1878.55  292.65 1935.95  292.85 1968.74  300.28
 2001.52  301.98 2086.77  297.12 2244.15  298.17 2319.56  294.86 2352.34  296.02
 2365.46  299.02 2444.14  301.16 2506.44  316.95 2545.78  330.55 2572.01  345.87
#Mann= 3 , 0 , 0
  668.25     .12       0 1848.34    .045       0 1878.55     .12       0
Bank Sta=1848.34,1878.55
XS Rating Curve= 0 ,0
Exp/Cntr=0.3,0.1

Type RM Length L Ch R = 1 ,14429.5 ,520.55,505.74,490.63
XS GIS Cut Line= 3
 2458895.2024841 298985.763772322459228.01190928297485.996815264
2459360.93040653296885.634468848
#Sta/Elev= 30
  248.95  334.62  327.56  311.39  373.42  302.82  543.75  308.05  586.33  301.24
  664.95  298.03  681.33  291.44   953.2  291.31 1401.96  291.42 1418.34  299.69
 1431.44  301.68 1546.09  301.58 1569.01  295.07 1605.05  293.51  1624.7   301.5
 1664.01  301.94 1709.86   297.6 1814.64  299.67 1834.27  291.76 1959.93  291.51
 1989.91  291.48 2059.95  291.52 2076.31   295.8 2102.47  296.39 2190.78  295.95
 2220.22  292.62 2236.58  295.57  2279.1  293.89  2334.7  305.46 2400.12  333.92
#Mann= 3 , 0 , 0
  248.95     .12       0 1959.93    .045       0 1989.91     .12       0
Bank Sta=1959.93,1989.91
XS Rating Curve= 0 ,0
Exp/Cntr=0.3,0.1

Type RM Length L Ch R = 1 ,13923.76,482.49,494.26,505.93
XS GIS Cut Line= 3
2459875.38694679298768.7955180632459802.66692795297873.363822684
2459731.03647428296991.350844748
#Sta/Elev= 30
  101.64  359.01   170.5   306.3  177.05  304.01  196.73  306.25  206.56  293.07
   216.4  290.29  744.28  289.49  760.67  292.81   832.8  295.44  855.76  292.23
  878.71  295.69  921.33  295.08  950.84  301.14 1052.46  298.97 1081.96  294.26
 1140.95  298.14 1252.39  298.46 1294.99  294.43 1419.54  295.58 1486.51   287.6
  1516.5  287.51 1530.97  287.48 1563.74  287.54 1606.35  299.44 1622.74  299.23
 1675.18  289.63 1707.95   293.2 1806.28  321.77 1865.27  350.55 1884.93   364.4
#Mann= 3 , 0 , 0
  101.64     .12       0 1486.51    .045       0  1516.5     .12       0
Bank Sta=1486.51,1516.5
XS Rating Curve= 0 ,0
Exp/Cntr=0.3,0.1

Type RM Length L Ch R = 1 ,13429.5 ,876.1,885.57,895.03
XS GIS Cut Line= 3
2460058.73993413298655.1921217292460176.42044553 297893.76798135
2460278.06500526297236.100566029
#Sta/Elev= 30
   229.5  333.15  242.61  326.97  268.84  305.16  285.24  304.75  288.51  302.48
  298.35  290.35  304.91  289.05  803.25  288.36  816.36  288.67  842.59  294.39
   872.1  291.67  901.61  294.72  937.67  295.61  990.13  293.67 1003.24  291.51
 1019.63  294.22 1049.14  293.74 1062.25  297.23 1088.48  300.06 1170.43  295.44
 1193.38  296.84 1229.44  295.63 1298.29  298.72  1386.8  291.44 1419.58  286.14
 1471.22  286.38 1501.22  286.53 1547.44  287.37 1573.66  293.74 1665.45  333.22
#Mann= 3 , 0 , 0
   229.5     .12       0 1471.22    .045       0 1501.22     .12       0
Bank Sta=1471.22,1501.22
XS Rating Curve= 0 ,0
Exp/Cntr=0.3,0.1

Type RM Length L Ch R = 1 ,12924.04,376.92,380.11,383.31
XS GIS Cut Line= 3
2460359.81049868298859.5511547772460647.53498887297853.948835269
2460922.57741778296892.671230271
#Sta/Elev= 30
       0  485.29   52.46  471.33   91.81  451.78   170.5  403.36   295.1  307.22
  314.77  303.74     341  288.16 1101.68  284.41 1157.41  297.32 1213.14  290.86
 1242.65  296.94  1295.1  298.09 1331.16  287.41 1347.55   288.7 1360.66  284.02
 1396.67  284.11 1426.73   284.2  1475.4  284.78  1504.9  294.76  1521.3  305.36
 1573.75  329.12  1626.2  360.18 1639.31  368.64 1658.98  389.87 1724.54  418.31
  1760.6  438.09 1819.61   476.5 1872.06  500.11 1908.12  511.31 2045.81  536.21
#Mann= 3 , 0 , 0
       0     .12       0 1396.67    .045       0 1426.73     .12       0
Bank Sta=1396.67,1426.73
XS Rating Curve= 0 ,0
Exp/Cntr=0.3,0.1

Type RM Length L Ch R = 1 ,12543.93,597.27,656.78,714.79
XS GIS Cut Line= 3
2460704.84139671298747.9987298092461015.84888478297874.845775098
2461208.14307343 297334.98069087
#Sta/Elev= 30
  164.71  371.67  171.26  368.64  197.46  348.17  207.29  337.46  253.14  303.92
  276.07  302.65  289.17  289.47  308.82  289.55  318.65  286.76  970.41  282.23
 1022.82  285.79 1071.95  283.02 1088.32  284.07 1114.52  293.34 1173.47  297.93
 1232.41  297.15 1261.89  292.88 1288.08  295.69 1314.28  291.81  1350.3  281.11
 1384.65  281.11 1414.84  281.11 1425.62  281.36 1435.45  285.91 1448.55  284.42
 1461.65  290.27  1481.3  293.66 1576.26  322.21 1618.84  342.11 1664.68  371.94
#Mann= 3 , 0 , 0
  164.71     .12       0 1384.65    .045       0 1414.84     .12       0
Bank Sta=1384.65,1414.84
XS Rating Curve= 0 ,0
Exp/Cntr=0.3,0.1

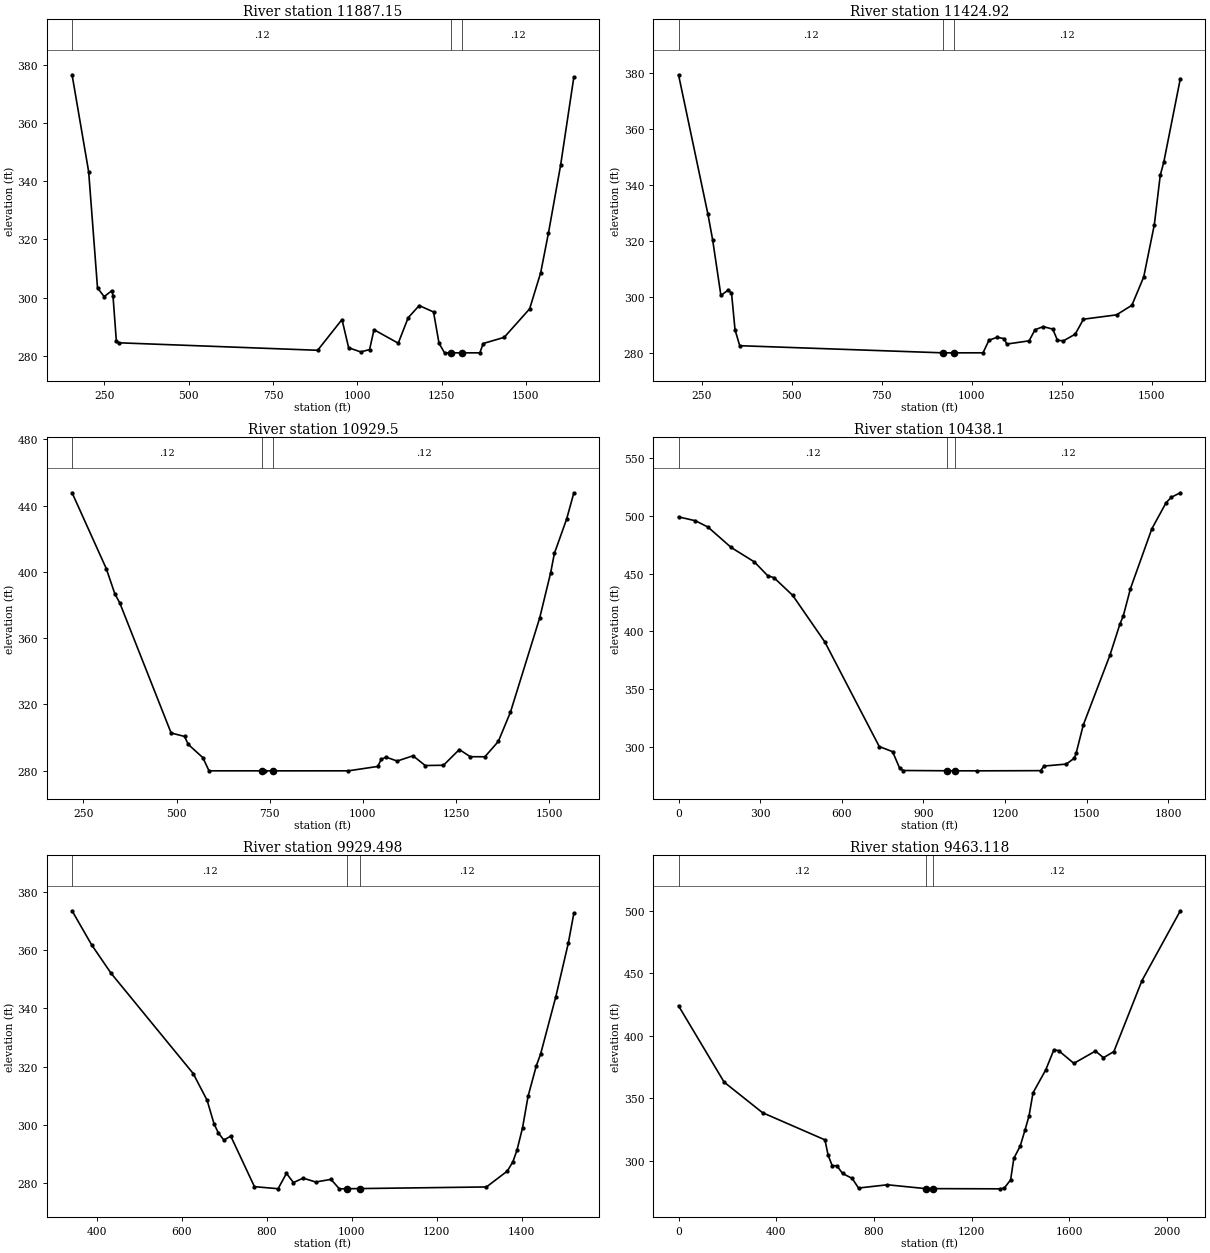
Type RM Length L Ch R = 1 ,11887.15,461.51,462.24,462.87
XS GIS Cut Line= 4
2460762.36028748298785.8641385142461139.11044927298057.421853527
2461475.22755919298038.5803557632461805.90019078298020.043915795
#Sta/Elev= 30
  154.18  376.52  203.39  343.25  229.63  303.35  249.31  300.37  272.27  302.43
  275.55  300.59   285.4  285.23  291.96  284.52  882.43  281.95   954.6   292.5
  974.29  282.81 1010.24  281.38 1036.38   282.2 1049.46  289.01 1121.36  284.38
 1150.78  293.12 1183.46   297.3 1225.95  295.11 1242.29  284.36 1258.63  281.07
 1279.24  281.07 1309.74  281.07 1363.39  281.07 1373.23  284.27 1435.53  286.39
 1510.95  296.17 1543.74  308.58 1566.69  322.15 1602.76  345.43 1642.11  375.78
#Mann= 3 , 0 , 0
  154.18     .12       0 1279.24    .045       0 1309.74     .12       0
Bank Sta=1279.24,1309.74
XS Rating Curve= 0 ,0
Exp/Cntr=0.3,0.1

Type RM Length L Ch R = 1 ,11424.92,514.76,495.42,475.69
XS GIS Cut Line= 4
2460850.08110829298872.1090007792461097.26768519298510.837285265
2461402.75395086298497.4422989342462051.31782329298469.003702475
#Sta/Elev= 30
  186.21  379.29  267.87  329.41  280.94  320.28  303.81  300.44  323.41  302.31
  333.21   301.4  343.01  288.17  356.08  282.49  919.97  279.94  950.19  279.94
 1031.37  279.95 1047.76  284.45 1070.72  285.51 1090.39  284.99 1096.94  283.07
 1159.24  284.23 1175.63  288.21 1198.58   289.3 1224.81  288.42 1237.93  284.43
 1254.32  284.22 1287.11   286.6 1310.06  291.96 1401.86  293.51 1444.48  296.94
 1477.27  307.04 1506.78  325.72 1523.17  343.38    1533  348.07 1578.91  377.91
#Mann= 3 , 0 , 0
  186.21     .12       0  919.97    .045       0  950.19     .12       0
Bank Sta=919.97,950.19
XS Rating Curve= 0 ,0
Exp/Cntr=0.3,0.1

Type RM Length L Ch R = 1 ,10929.5 ,489.35,500,510.61
XS GIS Cut Line= 3
2460942.44029895299205.4338169282461650.33810136298876.549808443
2462163.16605647298638.294057888
#Sta/Elev= 30
  219.74   447.8  311.57  401.98  334.53  386.76  347.65  381.34  485.39   302.8
  521.47  300.69  531.31  295.91  570.67  287.86  587.06  279.94   729.5  279.94
  737.93  279.93  759.17  279.93  960.95  279.94 1039.53  282.58 1049.33  286.94
 1062.41  288.18 1091.82  285.84 1134.32  289.01    1167  283.14 1216.03   283.3
 1258.52  292.78 1287.94  288.46 1327.16  288.43 1363.12  297.68  1395.8  315.44
 1474.25  372.35 1503.67  399.65 1513.47  411.17 1546.16  431.78 1565.77  447.75
#Mann= 3 , 0 , 0
  219.74     .12       0   729.5    .045       0  759.17     .12       0
Bank Sta=729.5,759.17
XS Rating Curve= 0 ,0
Exp/Cntr=0.3,0.1

Type RM Length L Ch R = 1 ,10438.1 ,1042.59,1008.6,973.6801
XS GIS Cut Line= 3
 2460642.2646582299769.7192819422461587.26408052299443.555892274
2462385.25756328299168.131574348
#Sta/Elev= 30
       0  499.03   62.28  495.67  108.16  490.23  193.39  472.57  278.61   460.1
  327.77  448.15  350.72  446.45  419.55  431.15  537.55  390.91  737.49  300.48
  786.65     296  812.87  281.54  825.98  279.73  985.12   279.5 1015.24  279.47
 1097.86  279.44 1330.18   279.6 1343.26  283.58 1425.07   285.3 1454.51  290.43
 1461.06  294.67 1487.23  319.07 1585.39  379.55 1621.39     406 1634.47  413.57
 1660.65  437.03 1739.18  488.71 1791.53  511.28 1811.16  516.04 1843.88  519.87
#Mann= 3 , 0 , 0
       0     .12       0  985.12    .045       0 1015.24     .12       0
Bank Sta=985.12,1015.24
XS Rating Curve= 0 ,0
Exp/Cntr=0.3,0.1

Type RM Length L Ch R = 1 ,9929.498,474.5,466.38,458.19
XS GIS Cut Line= 3
2461272.62091179300273.4638405822461810.85024753 299887.49693352
2462233.02215584299584.755677563
#Sta/Elev= 30
  340.99  373.65   386.9  361.96   432.8  352.14  626.25   317.6  659.03  308.39
  675.43  300.25  685.26  297.23  698.38  294.67  714.77  296.04  770.51  278.64
  826.25  277.93  845.92  283.22  862.32  280.05  885.27  281.58  914.78  280.24
  950.84  281.15  970.51  277.89  988.27  277.93 1018.28  277.98 1316.97  278.54
 1365.98     284 1379.05  287.15 1388.85  291.17 1401.92  298.91 1414.99  309.78
 1434.59  320.36 1444.39  324.25 1480.33  344.07 1509.74  362.51 1522.81  372.81
#Mann= 3 , 0 , 0
  340.99     .12       0  988.27    .045       0 1018.28     .12       0
Bank Sta=988.27,1018.28
XS Rating Curve= 0 ,0
Exp/Cntr=0.3,0.1

Type RM Length L Ch R = 1 ,9463.118,1111.17,1067.24,1022.03
XS GIS Cut Line= 3
 2461328.5034432300929.6651247742462078.07149786300269.047351524
2462869.91243386 299571.17407535
#Sta/Elev= 30
       0  424.11  186.72  363.02  343.96  338.58  599.48  316.84  612.58  304.51
  628.96  296.29  648.62   296.1  671.55  289.96  710.86  286.03  737.07  278.29
     855   280.9 1011.81  277.83 1042.33  277.82 1317.09  277.65 1333.48  278.19
 1359.71  284.81 1372.82  301.98 1399.04  311.92 1418.71  324.73  1435.1  335.98
 1451.49  354.46 1503.94  373.01 1536.72  388.84 1556.38  388.26 1618.66  378.07
 1707.17  387.92 1739.95  382.59 1782.56   387.5 1897.29  444.17 2054.63  500.16
#Mann= 3 , 0 , 0
       0     .12       0 1011.81    .045       0 1042.33     .12       0
Bank Sta=1011.81,1042.33
XS Rating Curve= 0 ,0
Exp/Cntr=0.3,0.1

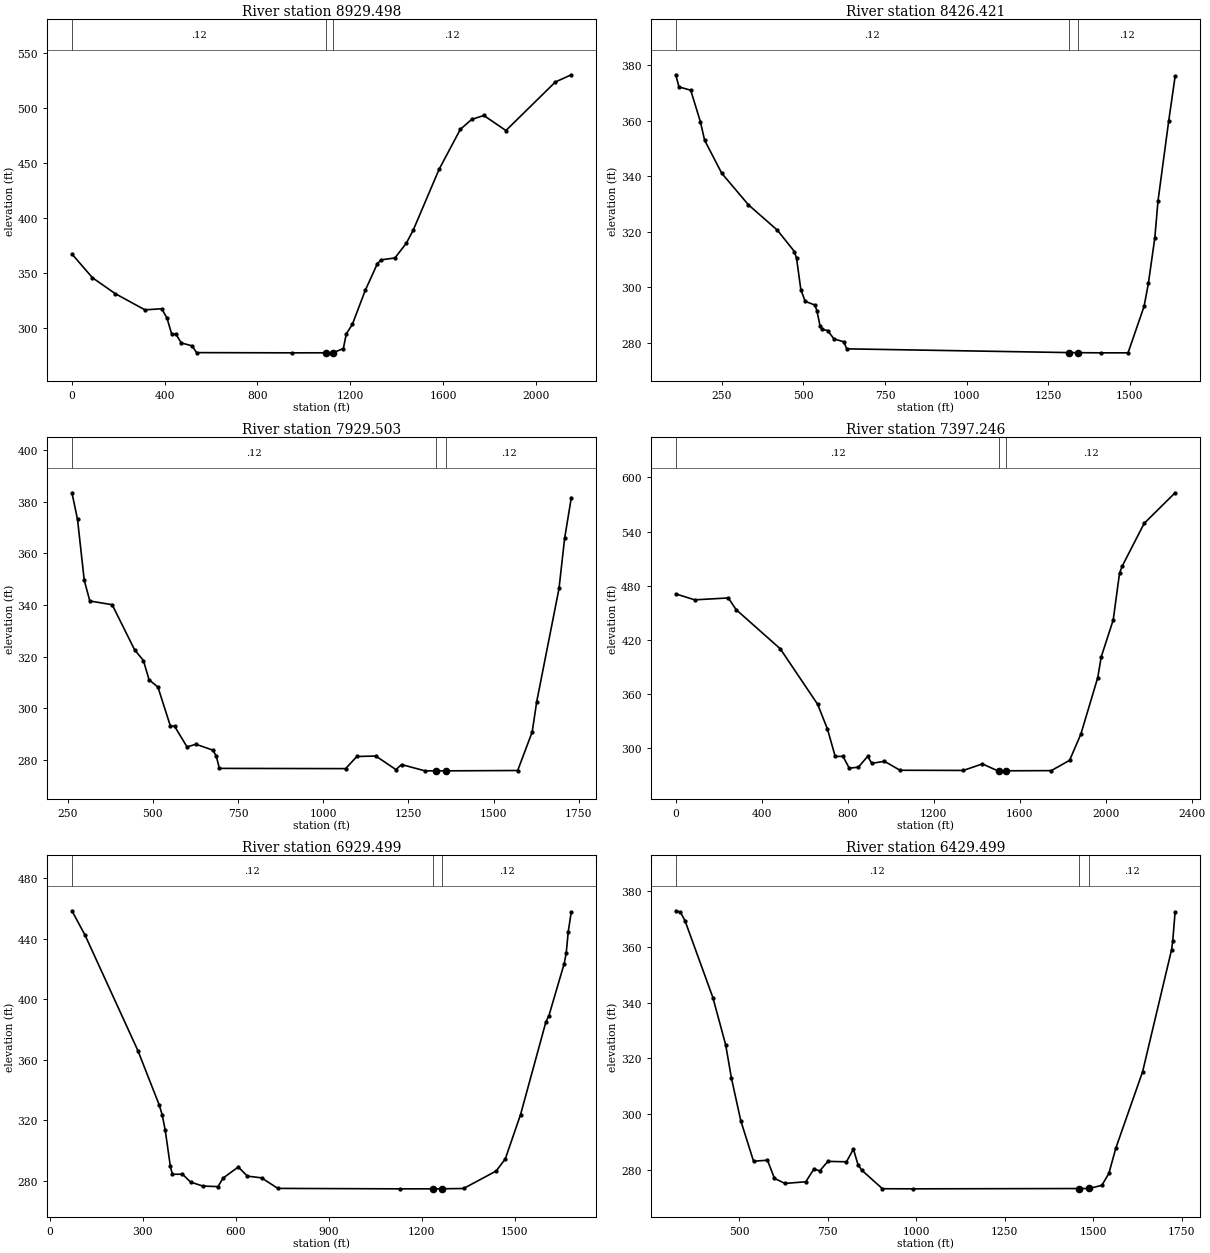
Type RM Length L Ch R = 1 ,8929.498,473.91,503.08,529.62
XS GIS Cut Line= 5
2461789.22069761301175.4900924412462562.47866553300506.471417353
2462594.41036019300424.5778803532462621.90768053300354.057352111
2463358.66506527299727.573368847
#Sta/Elev= 30
       0  367.41   88.49  345.86   186.8  331.39  314.62  316.67  386.72  317.66
  409.66  309.32  429.32   295.1  448.98  294.26  471.92  286.57  517.81  283.93
  537.47  277.78  950.41  277.58 1095.19  277.62 1125.68  277.64 1170.33   281.5
 1182.94  294.85 1209.05  303.44 1264.78  334.42 1317.23  358.77 1333.62  362.13
 1392.63  363.84  1441.8  377.27 1471.31  389.02 1582.77   444.3 1674.56  480.75
 1723.74  489.85 1776.19  493.37 1871.26  479.69 2084.35  523.82 2153.19  530.39
#Mann= 3 , 0 , 0
       0     .12       0 1095.19    .045       0 1125.68     .12       0
Bank Sta=1095.19,1125.68
XS Rating Curve= 0 ,0
Exp/Cntr=0.3,0.1

Type RM Length L Ch R = 1 ,8426.421,489.93,496.92,503.78
XS GIS Cut Line= 3
2462006.75066593301386.7460451742462741.52030219300825.192236602
2463223.52819765300456.813516811
#Sta/Elev= 30
  108.22  376.63  118.06  372.25  154.13  371.07  183.65  359.75  196.76  353.03
  249.23  341.13  331.22  329.73  419.76   320.6  472.23  312.88  478.79   310.4
  491.91  299.15  505.02  294.95  534.54  293.59   541.1  291.61  550.94  285.97
  557.49  284.83  573.89   284.4  593.57  281.36  623.08  280.35  632.92  277.79
 1313.08  276.44 1343.27  276.41  1413.4  276.35 1495.38  276.35 1544.57  293.14
 1557.68  301.39 1577.36  317.71  1587.2  331.12 1619.99  359.93 1639.66  376.02
#Mann= 3 , 0 , 0
  108.22     .12       0 1313.08    .045       0 1343.27     .12       0
Bank Sta=1313.08,1343.27
XS Rating Curve= 0 ,0
Exp/Cntr=0.3,0.1

Type RM Length L Ch R = 1 ,7929.503,1013.13,1000,983.7
XS GIS Cut Line= 3
2462315.87502149301585.6491247622462958.11501336301222.586783022
2463591.75046139300864.417431715
#Sta/Elev= 30
  262.32  383.47  278.71  373.14  298.38  349.63  314.78  341.59  380.36  340.15
  445.94  322.76  472.17  318.52  488.56  311.13  514.79  308.23  550.86  293.33
  563.98  293.03  600.05  285.11  626.28  286.14  675.46  283.88   685.3  281.78
  695.14   276.8 1065.65  276.71 1098.44   281.4 1154.18  281.58 1213.19  276.33
 1229.58  278.29 1298.44  275.85 1330.01  275.85 1359.96  275.85 1570.57  275.98
 1613.19  290.93  1626.3  302.54 1691.88  346.43 1708.27  365.78 1727.94  381.59
#Mann= 3 , 0 , 0
  262.32     .12       0 1330.01    .045       0 1359.96     .12       0
Bank Sta=1330.01,1359.96
XS Rating Curve= 0 ,0
Exp/Cntr=0.3,0.1

Type RM Length L Ch R = 1 ,7397.246,476.79,467.75,458.63
XS GIS Cut Line= 4
2462200.87833886302161.8995369372462627.88765544302149.447134018
2463350.71691844301628.6492910982464165.60472436301041.523496851
#Sta/Elev= 30
       0  470.93   88.05  464.32  244.57  466.42  280.45  453.55  486.15  410.08
  659.74  348.66   705.6  321.19  741.63  290.85  777.66  290.92  807.14  277.84
  849.72  278.96   892.3  290.89  911.95  283.23   970.9  285.45 1042.96  275.53
 1337.72  275.34 1426.06  282.56 1498.03  274.89 1505.71   274.9 1536.04  274.94
 1746.67  275.13 1831.73  286.54 1884.07   315.5 1962.59  378.11 1978.94  401.17
 2034.56  441.94    2064  493.79 2077.09  501.95 2178.51  548.98 2322.46  582.92
#Mann= 3 , 0 , 0
       0     .12       0 1505.71    .045       0 1536.04     .12       0
Bank Sta=1505.71,1536.04
XS Rating Curve= 0 ,0
Exp/Cntr=0.3,0.1

Type RM Length L Ch R = 1 ,6929.499,500.8,500,499.16
XS GIS Cut Line= 3
2463037.67069531302681.0885869452463680.85470961302010.323396519
2464152.84341023301518.095050898
#Sta/Elev= 30
   71.99  458.35  114.53  442.11  284.68  365.97   353.4  330.08  363.22  323.45
  373.03  313.23  389.39  289.57  395.94  284.15  428.66  284.24  454.84  279.02
   494.1   276.4  543.19  276.02  559.55  281.64  608.63  288.98  638.08  282.95
  683.89  281.81  736.25  274.84 1129.16  274.55 1236.66  274.56 1266.69  274.58
 1335.72  274.78 1440.63  286.32 1470.14  294.28 1519.32  323.52 1601.29  384.91
 1611.12  389.12  1660.3  423.45 1666.86  430.47 1673.41  444.59 1683.25  457.69
#Mann= 3 , 0 , 0
   71.99     .12       0 1236.66    .045       0 1266.69     .12       0
Bank Sta=1236.66,1266.69
XS Rating Curve= 0 ,0
Exp/Cntr=0.3,0.1

Type RM Length L Ch R = 1 ,6429.499,507.94,500,492.05
XS GIS Cut Line= 3
2463430.17791519303020.8389475232463891.84936635  302523.3660056
2464389.19984827301987.448208161
#Sta/Elev= 30
  321.31  372.87  334.43   372.4  347.54  369.29  426.23  341.77   462.3  324.88
  478.69  312.86  504.92  297.72  540.98  283.22  580.33  283.57     600  277.08
  629.51  275.27  688.53  275.86  711.48  280.43  727.87  279.75  750.82  283.16
  803.28  283.01  822.95  287.55  836.07  281.89   845.9  280.08  904.92  273.37
  990.17  273.33 1459.19  273.44 1489.19  273.46 1524.59  274.61 1544.27   278.9
 1563.94  287.96 1639.35  315.24 1721.32  358.99 1724.59  362.21 1731.15  372.47
#Mann= 3 , 0 , 0
  321.31     .12       0 1459.19    .045       0 1489.19     .12       0
Bank Sta=1459.19,1489.19
XS Rating Curve= 0 ,0
Exp/Cntr=0.3,0.1

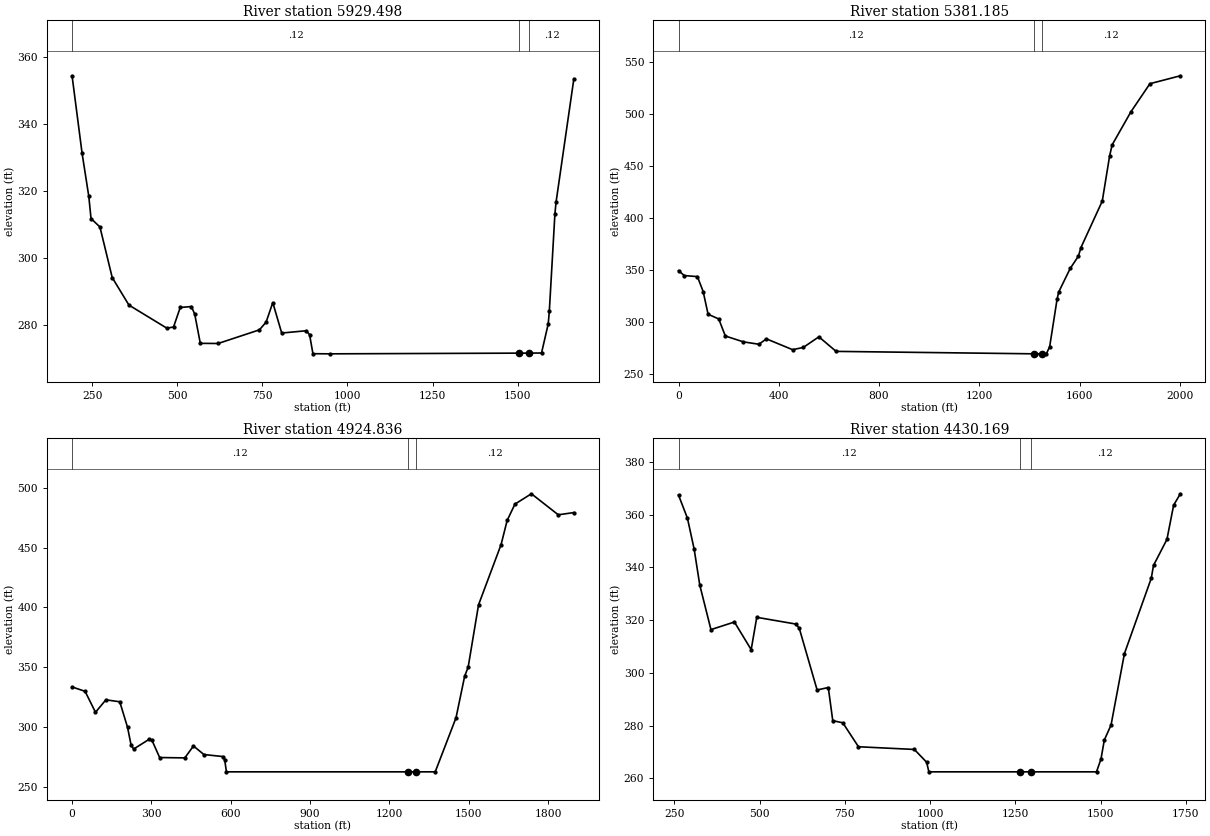
Type RM Length L Ch R = 1 ,5929.498,982.92,1000,1016.94
XS GIS Cut Line= 3
2463872.86065952303583.2340261232464322.85309753 302909.92363143
2464692.68168021302356.561244415
#Sta/Elev= 30
  190.16  354.51  219.67  331.33  239.34  318.52   245.9   311.9  272.13  309.37
   308.2  294.28  357.38  286.06  468.85  279.17  488.52  279.52   508.2  285.35
  540.98  285.63  550.82  283.36  567.21  274.64  619.67   274.6  740.98  278.67
  760.66  280.97  780.33   286.8  806.56  277.72  878.69   278.4  888.52  277.23
  898.36  271.55  947.54  271.51  1504.8  271.72 1534.78  271.73  1570.5  271.76
 1590.17  280.43 1593.45  284.26 1609.84  313.23 1613.12   316.7 1665.58  353.61
#Mann= 3 , 0 , 0
  190.16     .12       0  1504.8    .045       0 1534.78     .12       0
Bank Sta=1504.8,1534.78
XS Rating Curve= 0 ,0
Exp/Cntr=0.3,0.1

Type RM Length L Ch R = 1 ,5381.185,954.9,955.68,951.63
XS GIS Cut Line= 3
2464258.09371261303935.9566843512464832.83698569303115.156488687
2465406.41129786302296.025252938
#Sta/Elev= 30
       0  349.22   22.92  344.49   75.32  343.48   98.24  329.12  117.88  307.25
  160.45   302.7  186.65  286.29  258.69  280.66  320.91  278.34  350.38  283.56
  455.17  273.11  497.73  275.29  559.95   285.5  628.72  271.48  1418.8  269.13
 1424.97  269.12 1448.65  269.13 1467.59   269.2 1480.71  276.01 1510.21  321.58
 1516.77  328.64 1562.67  351.35 1595.46  363.17  1605.3  371.33 1690.54  416.17
 1720.05  459.85 1729.89   470.3 1805.29  502.31  1880.7  529.21 2002.01  536.84
#Mann= 3 , 0 , 0
       0     .12       0  1418.8    .045       0 1448.65     .12       0
Bank Sta=1418.8,1448.65
XS Rating Curve= 0 ,0
Exp/Cntr=0.3,0.1

Type RM Length L Ch R = 1 ,4924.836,513.36,494.67,480.58
XS GIS Cut Line= 5
2464573.29911894304065.0082635132465287.89086561303162.489727348
2465397.27680169303086.6283305142465457.90430512303035.539521933
2465793.14871337302619.695537359
#Sta/Elev= 30
       0  333.45   49.19  329.78   88.55  312.25  127.91  322.67  180.38  321.04
   209.9  299.61  223.02  285.02  232.86  281.52  291.89  289.73  301.73  289.05
  331.25  274.42  426.36  274.13  459.15  284.09  498.51  276.94  570.66  275.24
  577.22  272.49  583.78  262.47 1269.36  262.47 1299.29  262.47  1373.4  262.47
 1452.04  307.66 1484.81  342.51 1497.92  349.94 1537.25  402.11 1622.45  452.43
 1645.39  472.59 1674.88  486.29 1737.14  494.92 1838.73  477.35 1897.71   479.2
#Mann= 3 , 0 , 0
       0     .12       0 1269.36    .045       0 1299.29     .12       0
Bank Sta=1269.36,1299.29
XS Rating Curve= 0 ,0
Exp/Cntr=0.3,0.1

Type RM Length L Ch R = 1 ,4430.169,532.18,512.44,492.49
XS GIS Cut Line= 3
2465180.66372231304279.3715439732465591.39747643303666.990030691
2466000.30353297 303057.33308851
#Sta/Elev= 30
  262.18   367.4  288.39  358.59  308.06  346.86  324.44   333.3  357.22   316.4
  426.04  319.28   475.2   308.8  491.58  321.06  606.28   318.5  616.12  316.95
  668.55  293.51  701.32  294.44  714.43  281.88  743.93  281.06  789.81  271.98
  953.67  270.96  989.71  266.11  996.27  262.47 1264.03  262.47 1294.37  262.47
 1487.84  262.47 1500.95  267.32 1510.78  274.54 1530.45  280.21 1569.77  307.33
 1648.43  335.87 1654.98  340.74 1694.31  350.58 1713.97  363.56 1733.63   367.9
#Mann= 3 , 0 , 0
  262.18     .12       0 1264.03    .045       0 1294.37     .12       0
Bank Sta=1264.03,1294.37
XS Rating Curve= 0 ,0
Exp/Cntr=0.3,0.1