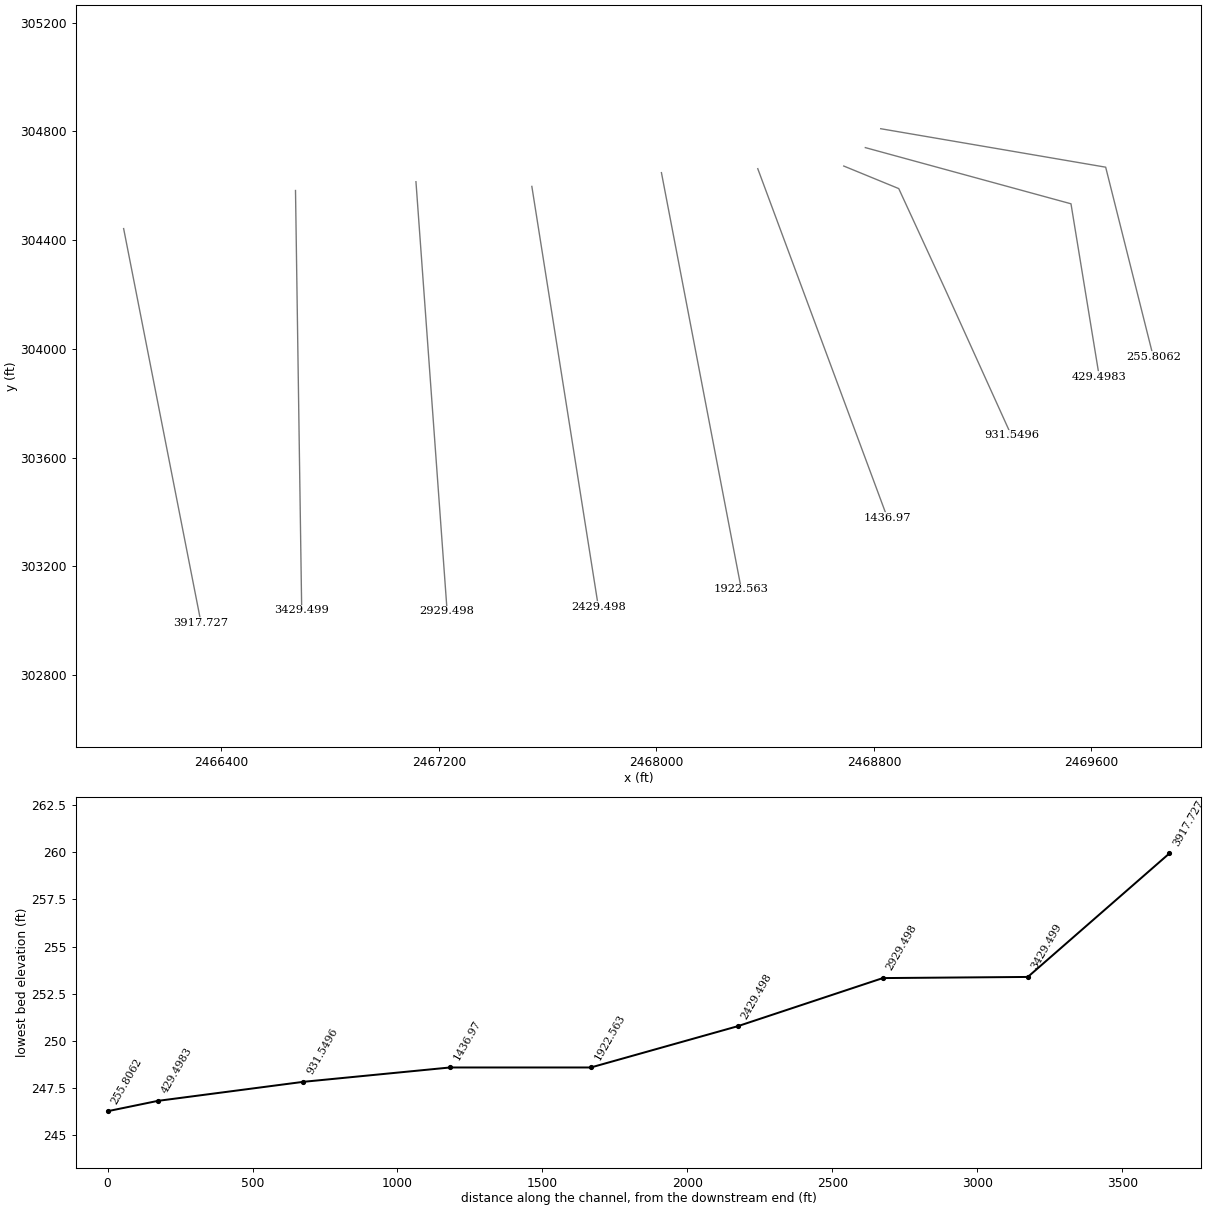
HEC-RAS study Shenandoah2.prj: Shenandoah2

--- Shenandoah2.g01 (geometry) --- (continued)

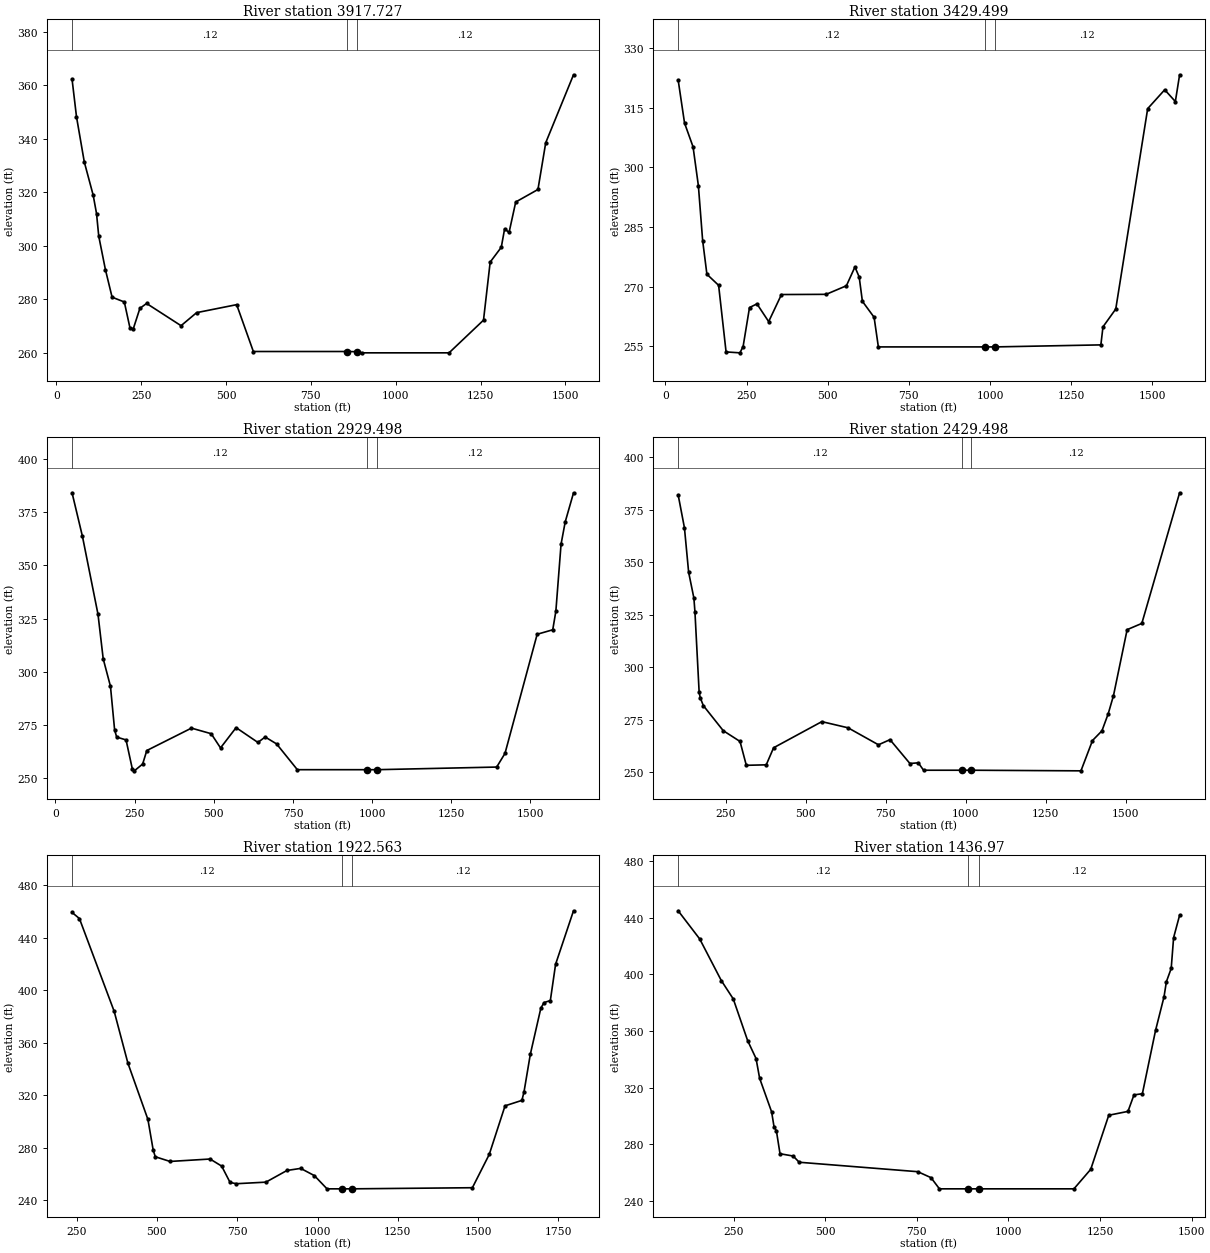
Type RM Length L Ch R = 1 ,3917.727,497.19,488.23,479.22
XS GIS Cut Line= 3
2466040.89099275304442.1019179212466224.71084236303505.903738692
2466325.68759877302991.628056867
#Sta/Elev= 30
    45.9  362.28   59.01  348.22   81.96  331.34  108.19   318.9  118.03  312.05
  124.59  303.58  144.26  291.04  163.93  280.75  199.99  278.96  216.39  269.38
  226.22  268.86   245.9  276.58  265.57  278.41   367.2  270.09   413.1  274.97
  531.13  277.96  580.31  260.44  856.59  260.44  886.76  260.36  901.61  259.94
  1157.2  259.94 1258.74  272.16 1278.39  293.87 1311.15  299.42 1320.97  306.31
 1334.08  304.96 1353.73  316.35 1419.24  321.03 1442.17  338.52 1524.06  363.93
#Mann= 3 , 0 , 0
    45.9     .12       0  856.59    .045       0  886.76     .12       0
Bank Sta=856.59,886.76
XS Rating Curve= 0 ,0
Exp/Cntr=0.3,0.1

Type RM Length L Ch R = 1 ,3429.499,497.11,500,502.88
XS GIS Cut Line= 3
2466672.97205906304582.1647329212466687.15676786303621.094453186
2466695.76774639303037.666337085
#Sta/Elev= 30
   39.37  322.01   59.05  311.17   85.29  305.19  101.69  295.42  114.82  281.63
  127.94  273.15  164.02  270.37  186.99  253.62  229.63  253.39  239.47  254.98
  259.16  264.78  282.12   265.7  318.21  261.24  357.57  268.05  495.35   268.1
  557.68  270.26  583.92  274.99  597.05  272.46  606.89  266.35  642.97  262.33
  656.09  254.88  985.54  254.88 1015.51  254.88 1341.46  255.39 1348.02  259.93
 1387.36  264.41  1485.7   314.8 1538.15  319.54 1570.93  316.58 1584.04  323.31
#Mann= 3 , 0 , 0
   39.37     .12       0  985.54    .045       0 1015.51     .12       0
Bank Sta=985.54,1015.51
XS Rating Curve= 0 ,0
Exp/Cntr=0.3,0.1

Type RM Length L Ch R = 1 ,2929.498,495.77,500,504.22
XS GIS Cut Line= 3
2467115.92283086304614.4464470342467184.50058945303669.391600683
2467230.53206958303035.043037642
#Sta/Elev= 30
   52.46  384.23   85.25  363.72  134.43     327  150.82  306.07  173.77  293.13
  186.89  272.55  193.44  269.21  222.95  267.89  242.62  254.35  249.18  253.33
  275.41  256.54  288.52  262.89  429.51  273.44   491.8  270.81  521.31  264.12
  570.49  273.67  639.34   266.7   662.3  269.26  698.36  266.01  763.94  253.87
     985  253.87    1015  253.87 1393.41  255.11 1419.64  261.54 1521.27  317.63
 1570.45  319.73 1580.28  328.47 1596.67  360.01 1609.79  370.51 1636.02  384.17
#Mann= 3 , 0 , 0
   52.46     .12       0     985    .045       0    1015     .12       0
Bank Sta=985,1015
XS Rating Curve= 0 ,0
Exp/Cntr=0.3,0.1

Type RM Length L Ch R = 1 ,2429.498,505.3,506.94,508.55
XS GIS Cut Line= 3
2467542.12299488304597.2433118162467682.89460577 303707.59231168
2467786.89047628303050.357311322
#Sta/Elev= 30
  101.54  382.05  121.19  366.37  134.29  345.22  150.67  332.96  153.94   326.5
  167.04  288.35  170.32  285.66  180.14  281.82  242.38  269.88  294.78  264.76
  314.43  253.41  376.67  253.64  399.59  261.75  550.26  274.18  632.14  271.25
  727.13  263.17  763.16  265.61  825.39  254.27  851.59   254.6  867.97  251.07
  987.23  251.07 1017.24  251.07 1359.56  250.78 1395.61   265.2 1425.11  269.81
 1444.78  277.96 1461.17  286.56 1503.79  317.93 1549.68   320.9 1667.68  383.03
#Mann= 3 , 0 , 0
  101.54     .12       0  987.23    .045       0 1017.24     .12       0
Bank Sta=987.23,1017.24
XS Rating Curve= 0 ,0
Exp/Cntr=0.3,0.1

Type RM Length L Ch R = 1 ,1922.563,477.25,485.59,493.86
XS GIS Cut Line= 3
2468018.68859502304647.8428573282468162.58065428303897.484976515
2468312.61930081303115.073576872
#Sta/Elev= 30
  236.09  459.17  259.05  454.51  367.26  383.77  409.89  344.37  472.19  301.48
  488.58  278.18  495.14  273.03  541.05  269.46  665.65  271.31  701.72  265.91
  727.96  253.44  747.63   252.5  839.44  253.69  905.03  262.59  947.65  264.17
  990.28  258.66 1029.62  248.59 1076.46  248.59 1106.46  248.59 1482.05  249.44
  1534.5  274.79 1583.68  311.83 1636.13  315.98 1642.69   322.4 1662.36  351.08
 1695.14  386.28 1704.98   390.5 1724.65  392.04 1741.04  419.72 1796.78  460.44
#Mann= 3 , 0 , 0
  236.09     .12       0 1076.46    .045       0 1106.46     .12       0
Bank Sta=1076.46,1106.46
XS Rating Curve= 0 ,0
Exp/Cntr=0.3,0.1

Type RM Length L Ch R = 1 ,1436.97 ,501.86,505.42,508.83
XS GIS Cut Line= 3
2468372.96301026304662.4074134852468603.02563952304042.907914013
 2468849.5766056303379.010203469
#Sta/Elev= 30
   98.14  444.88  157.03  424.97  215.92  395.63  248.63  382.64  287.89   353.2
  310.79  340.59   320.6  326.62  353.32  302.92  359.86  292.47   366.4  289.49
  376.22  273.37   412.2  271.74  428.56  267.36  752.44  260.69  788.49  256.48
  811.44  248.59  888.54  248.59  918.37  248.59 1178.65  248.59 1224.55  262.37
 1273.73  300.54 1326.19  303.26 1342.58  314.89 1365.54  315.75  1401.6  360.55
 1424.55  384.06 1431.11  394.83 1444.22  404.17 1450.78  425.91 1467.18  441.71
#Mann= 3 , 0 , 0
   98.14     .12       0  888.54    .045       0  918.37     .12       0
Bank Sta=888.54,918.37
XS Rating Curve= 0 ,0
Exp/Cntr=0.3,0.1

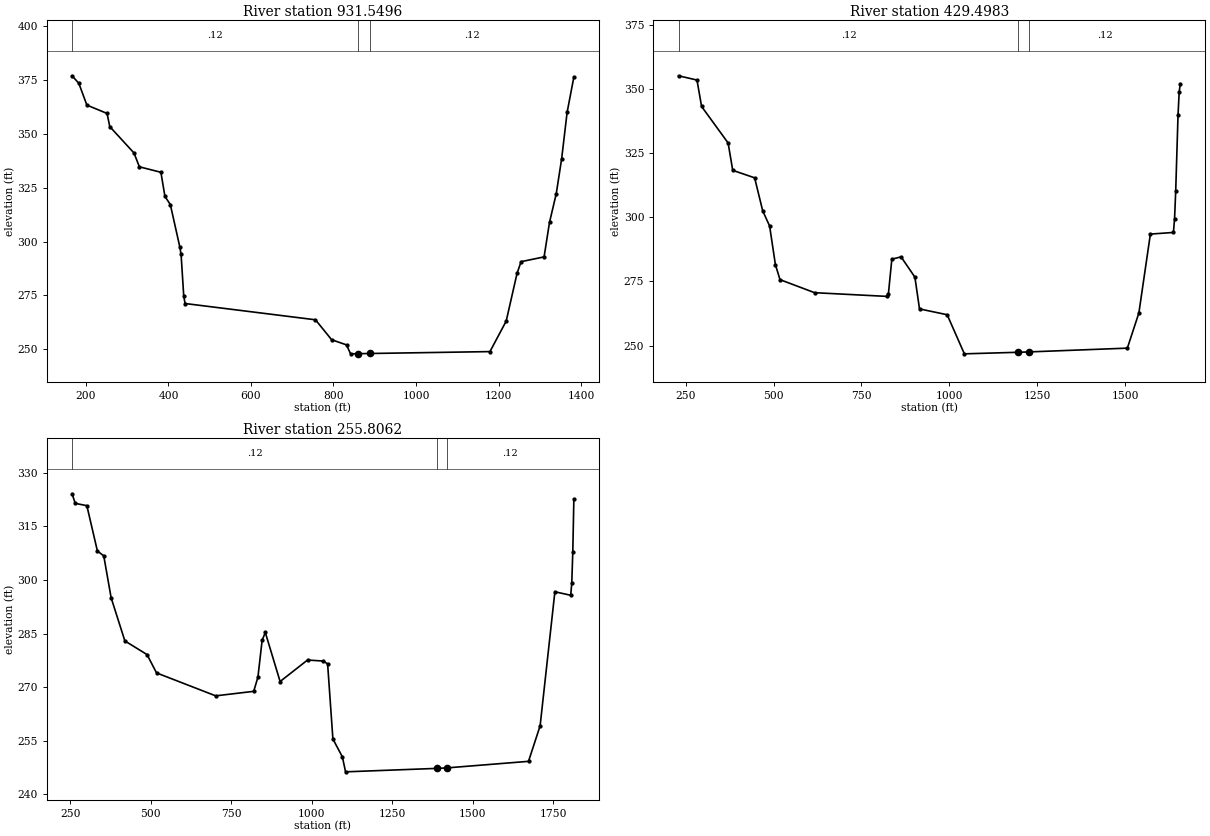
Type RM Length L Ch R = 1 ,931.5496,515.1,502.05,488.8
XS GIS Cut Line= 4
2468689.21000651304672.1600459832468891.43713619304589.192910686
2469061.93220203304219.3970623462469305.59891672303681.618726914
#Sta/Elev= 30
  166.38  377.03   182.7  373.56  202.27  363.41  251.21  359.53  257.73  353.42
  316.45  341.16   329.5  334.73   381.7  332.19  391.48  320.95  404.51  317.22
  427.31  297.67  430.57  294.11  437.09  274.53  440.34  271.21  756.34  263.65
  795.45  254.39  831.53  251.99  841.37  247.83  858.41  247.89   888.4  247.99
 1179.21  248.87 1218.57  263.04 1244.81  285.18 1254.65  290.66 1310.41  292.87
 1323.53   308.9 1339.93  322.27 1353.05  338.58 1366.17  359.97 1382.57  376.45
#Mann= 3 , 0 , 0
  166.38     .12       0  858.41    .045       0   888.4     .12       0
Bank Sta=858.41,888.4
XS Rating Curve= 0 ,0
Exp/Cntr=0.3,0.1

Type RM Length L Ch R = 1 ,429.4983,169.49,173.69,177.88
XS GIS Cut Line= 4
2468768.52245944304739.8996713142469524.87058061 304533.27701202
2469556.83639595304337.8974815162469628.80637239303898.006337226
#Sta/Elev= 30
  229.64  355.13  282.13  353.46  295.25  343.17  370.71  328.96  383.83   318.3
  446.16  315.38  469.12  302.53  488.81   296.6  505.21  281.59  518.33  275.72
  616.75  270.64  823.43  269.19  826.71  270.07  836.55  283.68   862.8   284.6
  902.16   276.7  915.29  264.32  994.02  262.05 1042.91  246.82 1196.69  247.43
 1226.67  247.57 1506.66  249.04 1539.43  262.71 1572.21  293.47 1637.76   294.1
 1641.03  299.44 1644.31  310.37 1650.87  339.71 1654.14  348.83 1657.42  352.02
#Mann= 3 , 0 , 0
  229.64     .12       0 1196.69    .045       0 1226.67     .12       0
Bank Sta=1196.69,1226.67
XS Rating Curve= 0 ,0
Exp/Cntr=0.3,0.1

Type RM Length L Ch R = 1 ,255.8062,258.29,255.81,263.11
XS GIS Cut Line= 4
2468825.12274977304809.3953239542469652.45464303304667.927333266
2469723.85115378304383.7008676082469827.53499842 303970.94113849
#Sta/Elev= 30
  255.74  324.13  265.57  321.45  301.64   320.8  334.43  308.09   354.1  306.76
  377.05     295  419.67  282.93  488.52   279.1  518.03  273.97  701.64  267.55
  819.67  268.81  832.78  272.78   845.9  283.14  855.73  285.29  901.64  271.56
  986.88  277.58 1036.06  277.29 1049.18  276.49 1065.57  255.48 1095.08  250.44
 1104.85  246.27 1388.85  247.24 1418.85  247.37 1672.95  249.21 1708.96  259.16
 1754.79  296.69  1803.9  295.71 1807.17  299.02 1810.44  307.94 1813.72  322.69
#Mann= 3 , 0 , 0
  255.74     .12       0 1388.85    .045       0 1418.85     .12       0
Bank Sta=1388.85,1418.85
XS Rating Curve= 0 ,0
Exp/Cntr=0.3,0.1

Chan Stop Cuts=-1

CM Alternative=Alternative #1
CM River Reach=ShenandoahRiver ,Reach2
 CM RS=14786.95,287.65,356.63,357.45,358.22,1863.45,test,287.65,,,
 CM RS=14429.5 ,986.48,520.55,505.74,490.63,1974.92,test,986.48,,,
 CM RS=13923.76,282.51,482.49,494.26,505.93,1501.51,test,282.51,,,
 CM RS=13429.5 ,281.38,876.1,885.57,895.03,1486.22,test,281.38,,,
 CM RS=12924.04,279.11,376.92,380.11,383.31,1411.7,test,279.11,,,
 CM RS=12543.93,276.11,597.27,656.78,714.79,1399.74,test,276.11,,,
 CM RS=11887.15,276.07,461.51,462.24,462.87,1294.49,test,276.07,,,
 CM RS=11424.92,274.94,514.76,495.42,475.69,935.08,test,274.94,,,
 CM RS=10929.5 ,274.93,489.35,500,510.61,744.33,test,274.93,,,
 CM RS=10438.1 ,274.47,1042.59,1008.6,973.6801,1000.18,test,274.47,,,
 CM RS=9929.498,272.93,474.5,466.38,458.19,1003.28,test,272.93,,,
 CM RS=9463.118,272.82,1111.17,1067.24,1022.03,1027.07,test,272.82,,,
 CM RS=8929.498,272.62,473.91,503.08,529.62,1110.44,test,272.62,,,
 CM RS=8426.421,271.41,489.93,496.92,503.78,1328.18,test,271.41,,,
 CM RS=7929.503,270.85,1013.13,1000,983.7,1344.98,test,270.85,,,
 CM RS=7397.246,269.9,476.79,467.75,458.63,1520.88,test,269.9,,,
 CM RS=6929.499,269.56,500.8,500,499.16,1251.68,test,269.56,,,
 CM RS=6429.499,268.44,507.94,500,492.05,1474.19,test,268.44,,,
 CM RS=5929.498,266.72,982.92,1000,1016.94,1519.79,test,266.72,,,
 CM RS=5381.185,264.12,954.9,955.68,951.63,1433.73,test,264.12,,,
 CM RS=4924.836,257.47,513.36,494.67,480.58,1284.32,test,257.47,,,
 CM RS=4430.169,257.47,532.18,512.44,492.49,1279.2,test,257.47,,,
 CM RS=3917.727,255.36,497.19,488.23,479.22,871.68,test,255.36,,,
 CM RS=3429.499,249.88,497.11,500,502.88,1000.53,test,249.88,,,
 CM RS=2929.498,248.87,495.77,500,504.22,1000,test,248.87,,,
 CM RS=2429.498,246.07,505.3,506.94,508.55,1002.23,test,246.07,,,
 CM RS=1922.563,243.59,477.25,485.59,493.86,1091.46,test,243.59,,,
 CM RS=1436.97 ,243.59,501.86,505.42,508.83,903.45,test,243.59,,,
 CM RS=931.5496,242.89,515.1,502.05,488.8,873.41,test,242.89,,,
 CM RS=429.4983,242.43,169.49,173.69,177.88,1211.68,test,242.43,,,
 CM RS=255.8062,243.24,258.29,255.81,263.11,1403.85,test,243.24,,,
CM Template=test,False, 0 , 1
 CM Simple Trapezoid=5,100,0,0.035
Use User Specified Reach Order=0
Composite Channel Slope=5